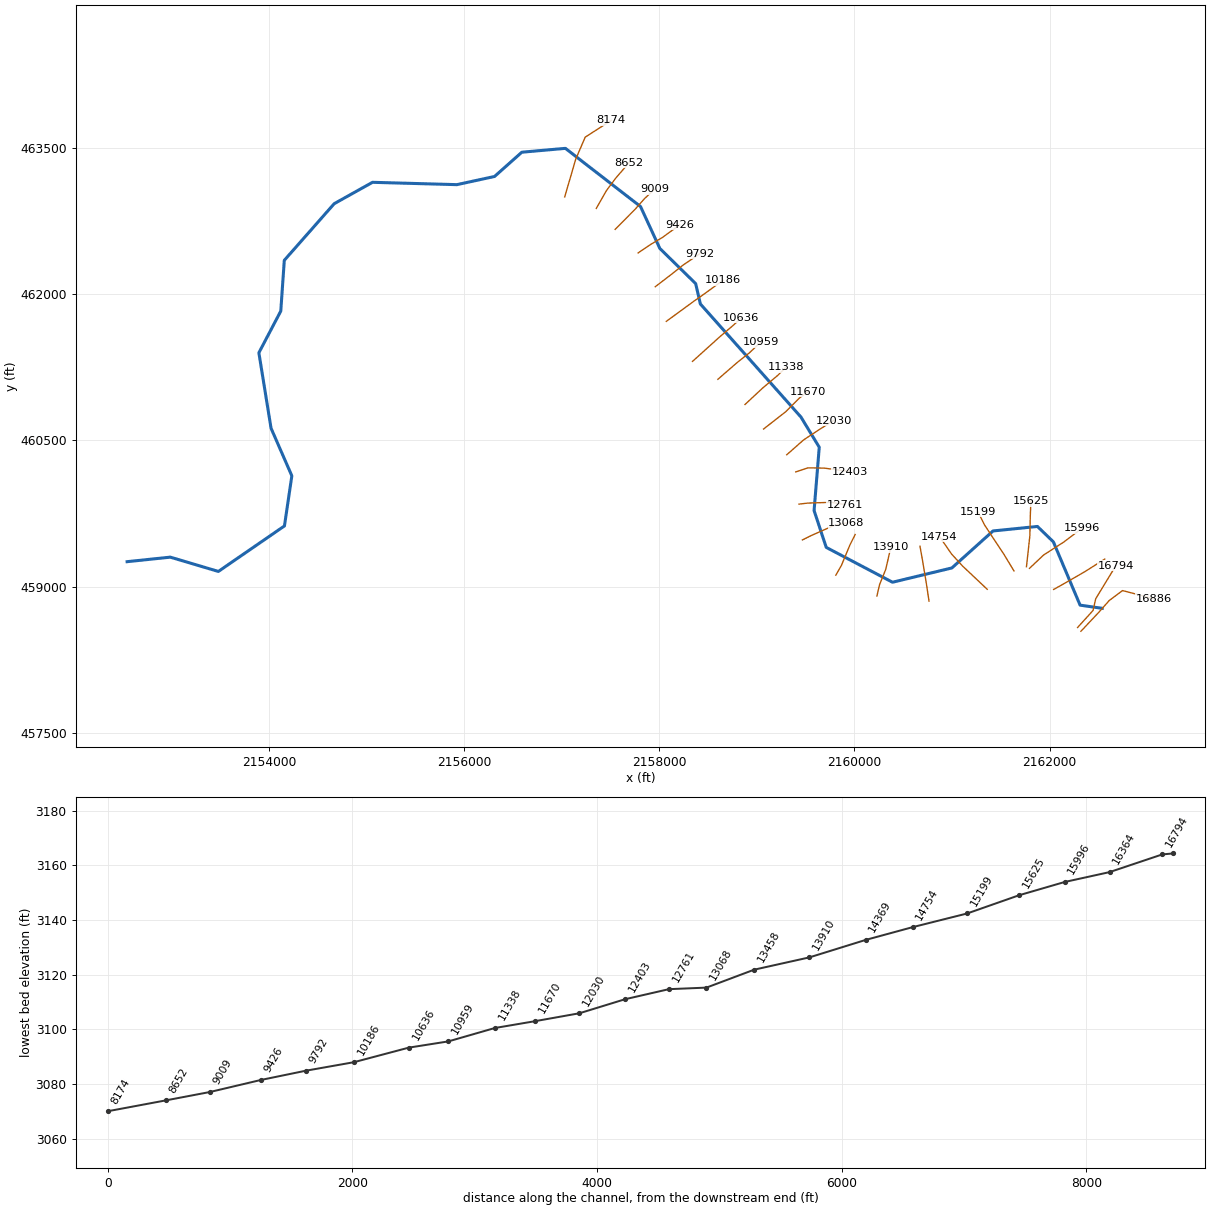
--- CRANBRYRV.prj (project) ---

Proj Title=CRANBRYRV
Current Plan=p01
Default Exp/Contr=0,0
English Units
Geom File=g01
Flow File=f01
Plan File=p01
Background Map Layer=Inundation Boundary (01pct Value_0)
Background Map Layer=QC
BEGIN DESCRIPTION:
----------MODEL BY WOOD PLC 2021----------
Stream Name: Cranberry River
Flood Zone: Approximate
Pocahontas County, WV
HEC-RAS Version: RAS 6.1
Vertical Datum: NAVD88
Projection: NAD 1983 StatePlane West Virginia S FIPS 4702 (US Feet)
Terrain: 1-meter LIDAR (FEMA Region III 3DEP collected 2016-2018)
Land Use: 2019 NLCD
Hydrologic Method:
Gage-Weighted WV 2010 RRE
Model Notes:
Model extends beyond county boundary on the downstream end
END DESCRIPTION:
DSS Export Rating Curves= 0
DSS Export Rating Curve Sorted= 0
DSS Export Volume Flow Curves= 0
DXF OffsetX= 0
DXF OffsetY= 0
DXF ScaleX= 0
DXF ScaleY= 0

--- CRANBRYRV.p01 (plan) ---

Plan Title=Floodplain
Program Version=6.10
Short Identifier=Floodplain
Geom File=g01
Flow File=f01
Subcritical Flow
K Sum by GR= 0
Std Step Tol= 0.01
Critical Tol= 0.01
Num of Std Step Trials= 20
Max Error Tol= 0.3
Flow Tol Ratio= 0.001
Split Flow NTrial= 30
Split Flow Tol= 0.02
Split Flow Ratio= 0.02
Log Output Level= 0
Friction Slope Method= 1
Unsteady Friction Slope Method= 2
Unsteady Bridges Friction Slope Method= 1
Parabolic Critical Depth
Global Vel Dist= 0 , 0 , 0
Global Log Level= 0
CheckData=True
Encroach Param=-1 ,0,0, 0
Mapping Interval=1HOUR
Computation Time Step Use Courant=        0
Computation Time Step Use Time Series=    0
Computation Time Step Count To Double=0
Computation Time Step Max Doubling=0
Computation Time Step Max Halving=0
Computation Time Step Residence Courant=0
Run HTab= 0
Run UNet= 0
Run Sediment= 0
Run PostProcess= 0
Run WQNet= 0
Run RASMapper= 0
UNET Theta= 0
UNET Theta Warmup= 0
UNET ZTol= 0
UNET ZSATol= 0
UNET MxIter= 0
UNET Max Iter WO Improvement= 0
UNET MaxInSteps= 0
UNET DtIC= 0
UNET DtMin= 0
UNET MaxCRTS= 0
UNET WFStab= 0
UNET SFStab= 0
UNET WFX= 1
UNET SFX= 1
UNET Gravity=32.174
UNET 1D Methodology=Finite Difference
UNET DSS MLevel= 1
UNET Pardiso=0
UNET DZMax Abort= 0
UNET Use Existing IB Tables= 0
UNET Froude Reduction=False
UNET Froude Limit= 0
UNET Froude Power= 0
UNET D1 Cores= 0
UNET WindReference=Eulerian
UNET WindDragFormulation=Hsu (1988)
UNET D2 Coriolis=0
UNET D2 Cores= 0
UNET D2 Theta= 1
UNET D2 Theta Warmup= 1
UNET D2 Z Tol= 0.01
UNET D2 Volume Tol= 0.01
UNET D2 Max Iterations= 20
UNET D2 Equation= 0
UNET D2 RampUpFraction=0.1
UNET D2 TimeSlices= 1
UNET D2 Turbulence Formulation=Non-Conservative (original)
UNET D2 Eddy Viscosity=0.3
UNET D2 Transverse Eddy Viscosity=0.1
UNET D2 Smagorinsky Mixing=0
UNET D2 BCVolumeCheck=0
UNET D2 Cores=0
UNET D2 SolverType=PARDISO (Direct)
UNET D2 Minimum Iterations= 2147483647
UNET D2 Maximum Iterations= 2147483647
UNET D2 Restart Number= 10
UNET D2 Relaxation Coeff=1.3
UNET D2 SOR Precondition Iterations= 10
UNET D2 ILUT Maximum Fill= 8
UNET D2 ILUT Tolerance=1E-08
UNET D1D2 MaxIter= 0
UNET D1D2 ZTol=0.01
UNET D1D2 QTol=0.1
UNET D1D2 MinQTol=1
Write IC File= 0
Write IC File at Fixed DateTime=0
Write IC File at Sim End=0
Echo Input=False
Echo Parameters=False
Echo Output=False
Write Detailed= 0
HDF Write Warmup=0
HDF Write Time Slices=0
HDF Flush=0
HDF Compression= 1
HDF Chunk Size= 1
HDF Spatial Parts= 1
HDF Use Max Rows=0
HDF Fixed Rows= 1
Calibration Method= 0
Calibration Iterations= 20
Calibration Max Change=0.05
Calibration Tolerance=0.2
Calibration Maximum=1.5
Calibration Minimum=0.5
Calibration Optimization Method= 1
WQ AD Non Conservative
WQ ULTIMATE=-1
WQ Max Comp Step=1HOUR
WQ Output Interval=15MIN
WQ Output Selected Increments= 0
WQ Output face flow=0
WQ Output face velocity=0
WQ Output face area=0
WQ Output face dispersion=0
WQ Output cell volume=0
WQ Output cell surface area=0
WQ Output cell continuity=0
WQ Output cumulative cell continuity=0
WQ Output face conc=0
WQ Output face dconc_dx=0
WQ Output face courant=0
WQ Output face peclet=0
WQ Output face adv mass=0
WQ Output face disp mass=0
WQ Output cell mass=0
WQ Output cell source sink temp=0
WQ Output nsm pathways=0
WQ Output nsm derived pathways=0
WQ Create Restart=0
WQ Fixed Restart=0
WQ System Summary=0
WQ Write To DSS=0
Sorting and Armoring Iterations= 10
XS Update Threshold= 0.02
Bed Roughness Predictor= 0
Hydraulics Update Threshold= 0.02
Energy Slope Method= 1
Volume Change Method= 1
Sediment Retention Method= 0
Sediment TS Multiplier= 1
Warm Up Method= 0
XS Weighting Method= 0
Number of US Weighted Cross Sections= 1
Number of DS Weighted Cross Sections= 1
Upstream XS Weight=0
Main XS Weight=1
Downstream XS Weight=0
Number of DS XS's Weighted with US Boundary= 1
Upstream Boundary Weight= 1
Weight of XSs Associated with US Boundary= 0
Number of US XS's Weighted with DS Boundary= 1
Downstream Boundary Weight= 0.5
Weight of XSs Associated with DS Boundary= 0.5
Percentile Method= 0
Sediment Output Level= 3
Mass or Volume Output= 0
Output Increment Type= 1
Profile and TS Output Increment= 1
Transport Output Increment 1
XS Output Flag= 0
XS Output Increment= 10
Read HDF5 Sediment Hotstart= 0
Sediment Hotstart Type= 0
Write Gradation File= 0
Read Gradation Hotstart= 0
Write HDF5 File= 1
Write Binary Output= 1
Write DSS Sediment File= 0
DSS Sediment Output Type= 1
SV Curve= 0
Specific Gage Flag= 0
Subcell Erosion Methods= 0
Subcell Deposition Methods= 0
Advection Scheme= 1
Matrix Solver= 0
Implicit Weighting Factor= 1
Maximum Outer Loop Convergence Iterations= 5
Convergence Maximum Absolute= 0.001
Convergence RMSE= 0.0001
Grain Fractions Max Abs Error= 0.001
Max Subgrid Regions= 1
Max Subgrid Length Scale= 3.402823E+38
Initial Layer Thickness= 3.402823E+38
Min Layer Thickness= 3.402823E+38
Max Layer Thickness= 3.402823E+38
Number of Layers= 5

--- CRANBRYRV.f01 (steady flow) ---

Flow Title=Flow
Program Version=6.10
Number of Profiles= 6
Profile Names=01pct,10pct,04pct,02pct,0_2pct,01plus
River Rch & RM=CRANBRYRVSF,Main            ,16886
    4220    2410    3080    3630    5670    6230
River Rch & RM=CRANBRYRVSF,Main            ,15199
    4730    2710    3460    4080    6350    6990
River Rch & RM=CRANBRYRVSF,Main            ,6275
    7970    4650    5890    6910   10900    9580
Boundary for River Rch & Prof#=CRANBRYRVSF,Main            , 1
Up Type= 0
Dn Type= 3
Dn Slope=0.010199
Boundary for River Rch & Prof#=CRANBRYRVSF,Main            , 2
Up Type= 0
Dn Type= 3
Dn Slope=0.010199
Boundary for River Rch & Prof#=CRANBRYRVSF,Main            , 3
Up Type= 0
Dn Type= 3
Dn Slope=0.010199
Boundary for River Rch & Prof#=CRANBRYRVSF,Main            , 4
Up Type= 0
Dn Type= 3
Dn Slope=0.010199
Boundary for River Rch & Prof#=CRANBRYRVSF,Main            , 5
Up Type= 0
Dn Type= 3
Dn Slope=0.010199
Boundary for River Rch & Prof#=CRANBRYRVSF,Main            , 6
Up Type= 0
Dn Type= 3
Dn Slope=0.010199
DSS Import GetInterval= 0
DSS Import GetPeak= 0
DSS Import FillOption= 0

--- CRANBRYRV.g01 (geometry) ---

Geom Title=Geometry
Program Version=6.10

River Reach=CRANBRYRVSF     ,Main
Reach XY= 30
2162541.04814982458776.891085487     2162313.412      458809.715
     2162039.538      459458.352     2161876.178      459616.206
     2161421.373      459570.107     2160999.183      459190.827
     2160390.846       459044.43     2159711.666      459401.597
     2159587.079      459778.928     2159640.038      460428.323
     2159452.494      460737.356     2158421.712      461896.336
     2158373.447      462105.075     2158006.013      462465.643
     2157808.245      462894.977     2157038.492      463491.349
        2156592.      463451.883     2156312.112      463203.162
     2155926.089      463119.387     2155061.314      463143.312
     2154668.531      462924.092     2154157.253      462343.698
     2154121.192      461823.693     2153896.677      461396.102
      2154021.46      460623.164     2154234.561      460134.887
     2154158.858      459621.536     2153481.548      459155.164
     2152988.991      459301.597     2152546.531      459255.179

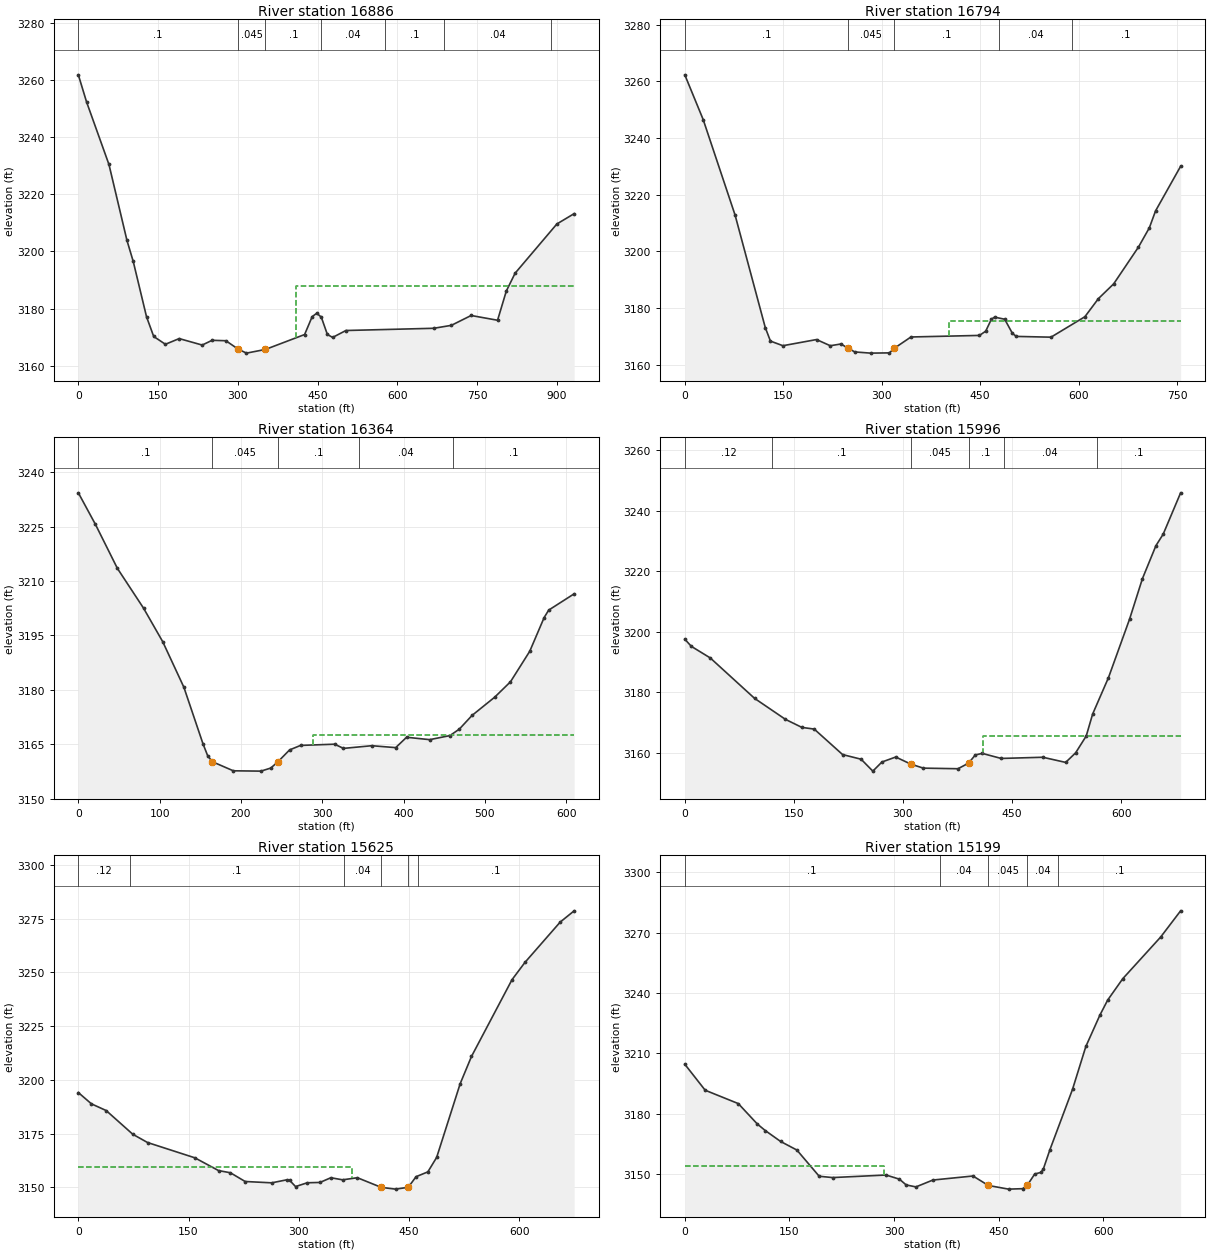
Type RM Length L Ch R = 1 ,16886   ,75.8,91.3,110.1
XS GIS Cut Line= 5
 2162322.0178905458541.952400622 2162507.6979477458739.094189747
2162610.85353503458856.0038553922162748.39431814458959.159442725
2163071.61515845458874.342626473
#Sta/Elev= 30
       0 3261.87    15.4 3252.42    57.6 3230.48    91.5 3203.87   103.3 3196.51
   128.3 3177.14   141.8 3170.24   163.8 3167.51   189.8  3169.5     233 3167.24
   251.7  3168.9   277.6 3168.75   300.3 3165.85   316.3 3164.41     352  3165.7
   425.7 3170.92   439.9 3177.18   448.5 3178.37   457.1 3177.02   468.5 3170.95
   478.4 3169.91   503.4 3172.33   668.7 3173.11   701.8 3174.14     739 3177.59
   788.7 3175.92   805.2 3186.16   821.7  3192.4   900.3 3209.64   932.8 3213.26
#Mann= 7 ,-1,0
       0      .1       0   300.3    .045       0     352      .1       0
  456.73     .04       0  576.73      .1       0  688.66     .04       0
  888.66      .1       0
#XS Ineff= 2 , 0
                           408.6         3188.07
Permanent Ineff=
       F       F
Bank Sta=300.3,352
XS Rating Curve= 0 ,0
Exp/Cntr(USF)=0,0
Exp/Cntr=0.3,0.1

Type RM Length L Ch R = 1 ,16794   ,463.1,430.7,393.7
XS GIS Cut Line= 4
2162287.79315897458580.4408964292162446.65276346458755.805394895
2162473.47321616458875.4658762022162679.78439083459213.816202654
#Sta/Elev= 30
       0 3262.27      28 3246.48    76.6 3212.79   122.6 3173.08   130.5 3168.29
   149.5 3166.66   200.7 3168.83   221.7 3166.65     238 3167.27  248.893165.737
   259.1 3164.46   283.1 3164.04   311.8 3164.13  319.123165.739   344.6 3169.74
     449 3170.29   458.5 3171.79   467.2 3176.03     472 3176.74   487.4 3176.01
   499.2 3171.02   505.1 3169.94     558 3169.67   609.6 3176.88   630.2 3183.27
   653.5 3188.49   691.3 3201.49   707.9  3208.3   717.3 3214.24   755.5 3229.99
#Mann= 5 ,-1,0
       0      .1       0  248.89    .045       0  319.12      .1       0
  479.25     .04       0  589.25      .1       0
#XS Ineff= 2 , 0
                           402.2         3175.27
Permanent Ineff=
       F       F
Bank Sta=248.89,319.12
XS Rating Curve= 0 ,0
Exp/Cntr(USF)=0,0
Exp/Cntr=0.3,0.1

Type RM Length L Ch R = 1 ,16364   ,365.3,367.6,370.2
XS GIS Cut Line= 4
2162042.28286111458970.3690165482162159.88023067459036.388592441
2162364.12829359459153.9859620012162566.31324476459281.898890294
#Sta/Elev= 30
       0 3234.32    21.1 3225.59      48  3213.5    80.2 3202.51   103.8 3193.26
   129.8 3180.71   153.2 3165.18   159.1  3161.8  164.813160.167   190.6 3157.66
   224.6 3157.57   236.7 3158.42  245.553160.167   259.8 3163.42   273.3 3164.66
   315.2    3165   326.1 3163.84   360.9 3164.58   390.3 3164.05   403.7 3166.91
   432.1 3166.25     457 3167.37   468.6 3169.16   484.2 3172.93   512.1 3177.97
   531.5 3182.21   555.2 3190.63   572.9 3199.93   578.5 3201.98   609.8 3206.47
#Mann= 5 ,-1,0
       0      .1       0  164.81    .045       0  245.55      .1       0
  344.86     .04       0  460.54      .1       0
#XS Ineff= 2 , 0
                          288.01         3167.42
Permanent Ineff=
       F       F
Bank Sta=164.81,245.55
XS Rating Curve= 0 ,0
Exp/Cntr(USF)=0,0
Exp/Cntr=0.3,0.1

Type RM Length L Ch R = 1 ,15996   ,342.3,371.2,409
XS GIS Cut Line= 4
2161794.70945151459186.9957499482161939.12727378459323.161125227
2162147.50156019 459457.263388762162335.24472914 459599.61809928
#Sta/Elev= 30
       0 3197.52       9 3195.15      35 3191.33      96 3177.97   138.4 3171.05
     161 3168.39     178 3167.83     217 3159.42   242.5 3157.88   258.6 3153.95
   271.1 3156.96   290.1 3158.61   310.7 3156.28     328 3154.94   375.7 3154.74
  390.353156.596   399.5 3159.29     409 3159.81   435.1 3158.14   492.4 3158.53
   523.8 3156.83   537.5 3159.99   552.1 3165.56   560.9  3172.8   582.7 3184.84
   611.7 3204.15   629.4 3217.53   647.9 3228.38     658 3232.24   681.9 3245.85
#Mann= 6 ,-1,0
       0     .12       0     120      .1       0   310.7    .045       0
  390.35      .1       0  438.49     .04       0  566.28      .1       0
#XS Ineff= 2 , 0
                          410.75         3165.41
Permanent Ineff=
       F       F
Bank Sta=310.7,390.35
XS Rating Curve= 0 ,0
Exp/Cntr(USF)=0,0
Exp/Cntr=0.3,0.1

Type RM Length L Ch R = 1 ,15625   ,406.7,426.1,448.2
XS GIS Cut Line= 4
2161763.76277531459203.5006439212161798.83567501459523.282964653
 2161802.9618985459721.3416923332161809.15123374459876.075073332
#Sta/Elev= 30
       0 3194.07    17.8 3188.82    37.9 3185.69    74.1 3174.66    94.2 3170.81
   158.6 3163.69   190.8 3157.75   206.9 3156.74     227 3152.67   263.2 3152.05
   283.4 3153.44   287.4 3153.25   295.6 3150.31   311.5 3152.08   328.8 3152.23
   343.6 3154.42   359.6 3153.45   379.7 3154.43   412.2 3149.94   431.6 3149.12
   448.9 3149.97   459.6 3154.91   475.6 3157.15   487.6 3163.88   519.6  3198.2
     535 3210.88   590.1 3246.58   607.7 3254.63   655.7 3273.41   674.7 3278.65
#Mann= 6 ,-1,0
       0     .12       0      70      .1       0   361.7     .04       0
   412.2    .045       0   448.9     .04       0   461.7      .1       0
#XS Ineff= 2 , 0
          372.36  3159.3
Permanent Ineff=
       F       F
Bank Sta=412.2,448.9
XS Rating Curve= 0 ,0
Exp/Cntr(USF)=0,0
Exp/Cntr=0.3,0.1

Type RM Length L Ch R = 1 ,15199   ,437.1,444.9,448.7
XS GIS Cut Line= 4
2161635.84984702459160.1752972412161534.75737143 459327.28734872
2161334.63553201 459630.564775482161266.55284437459766.730150759
#Sta/Elev= 30
       0 3204.56    29.2 3191.63    76.7 3184.98     104 3174.82   115.3 3171.58
   137.4 3166.14   160.7 3161.87   192.7 3148.83     212 3148.18   288.6 3149.45
   307.8 3147.37   317.4 3144.51   331.4 3143.54   355.7 3146.95   413.2 3148.96
   435.3 3144.24   464.2 3142.43   484.4 3142.65  490.873144.256   501.7 3149.95
   510.4 3150.73   513.9 3152.27   523.5 3162.04   555.9 3192.07     575 3213.38
   595.2 3229.02   606.3 3236.47     628 3247.13   682.3 3267.84   710.9 3280.87
#Mann= 5 ,-1,0
       0      .1       0  365.31     .04       0   435.3    .045       0
  490.87     .04       0  535.31      .1       0
#XS Ineff= 2 , 0
          286.03 3153.82
Permanent Ineff=
       F       F
Bank Sta=435.3,490.87
XS Rating Curve= 0 ,0
Exp/Cntr(USF)=0,0
Exp/Cntr=0.3,0.1

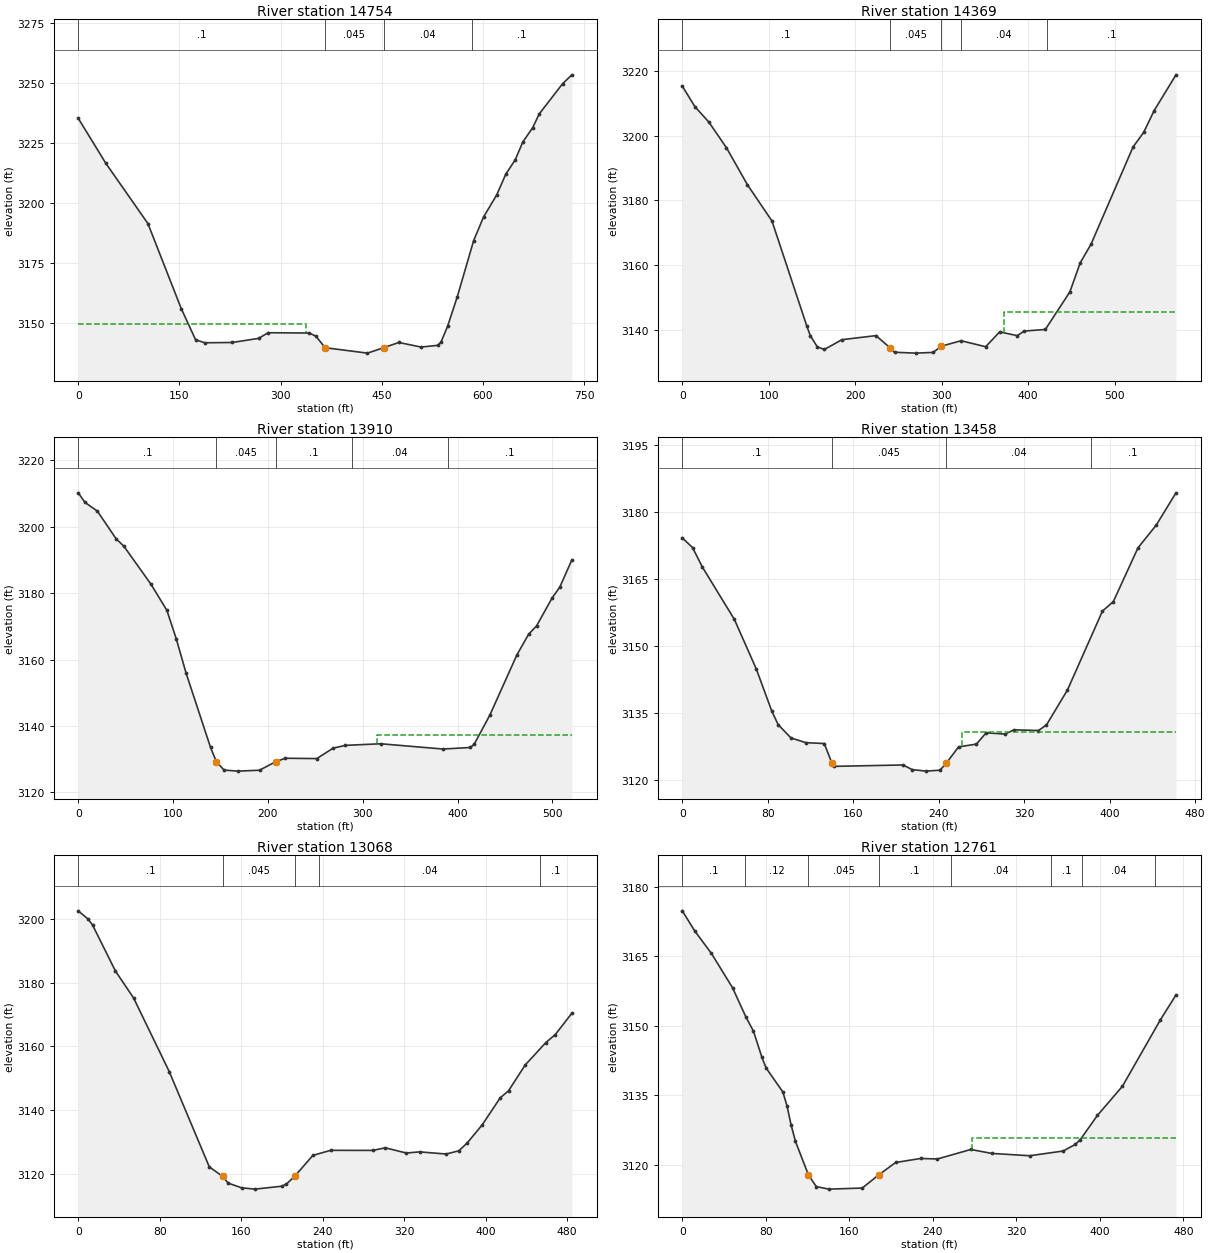
Type RM Length L Ch R = 1 ,14754   ,413.5,385.2,361.1
XS GIS Cut Line= 4
2161361.45598471458972.4321282952161109.75635162459209.689979161
2160996.28520556 459333.476683962160872.49850076 459512.96740592
#Sta/Elev= 30
       0 3235.33      41 3216.53   103.3 3191.46   152.7 3156.03     174 3143.02
   187.7 3141.75   228.5 3141.88   267.4 3143.59   281.6 3145.95   342.6 3145.81
   352.3 3144.51   366.13139.702   428.8 3137.44  452.823139.704   475.4 3141.88
   508.1 3139.97   532.9 3140.68   537.8 3142.01   547.5 3148.54     562 3160.93
   586.3 3184.38   600.9 3194.16   620.4 3203.36   633.8 3211.96   647.9 3218.03
   659.2 3225.48   673.8 3231.41   683.5 3237.15   718.3  3249.8   731.9 3253.44
#Mann= 4 ,-1,0
       0      .1       0   366.1    .045       0  452.82     .04       0
  583.82      .1       0
#XS Ineff= 2 , 0
          337.95  3149.7
Permanent Ineff=
       F       F
Bank Sta=366.1,452.82
XS Rating Curve= 0 ,0
Exp/Cntr(USF)=0,0
Exp/Cntr=0.3,0.1

Type RM Length L Ch R = 1 ,14369   ,479.7,458.5,434.2
XS GIS Cut Line= 4
2160765.21668993458850.7085352422160736.33312548459040.514815935
2160697.13400229459275.7095550542160672.37666133 459413.93804208
#Sta/Elev= 30
       0 3215.38    14.6 3209.02    30.8 3204.22    51.1  3196.3    75.3 3184.87
   103.7 3173.64   144.1 3141.04   148.2 3138.05   156.2 3134.67   164.3 3133.89
   184.6 3136.91     224 3138.17   240.13134.425   245.4 3133.02   269.7 3132.75
     290 3132.97   299.7 3134.91   322.4 3136.59   350.8 3134.73     367 3139.32
   387.4 3138.16   395.4 3139.58   419.8 3140.07   448.2  3151.7   460.1 3160.67
   472.6 3166.43   521.3 3196.57   533.5 3201.04   545.7 3207.83   570.9 3218.88
#Mann= 5 ,-1,0
       0      .1       0   240.1    .045       0   299.7      .1       0
  321.99     .04       0  421.99      .1       0
#XS Ineff= 2 , 0
                          371.62         3145.61
Permanent Ineff=
       F       F
Bank Sta=240.1,299.7
XS Rating Curve= 0 ,0
Exp/Cntr(USF)=0,0
Exp/Cntr=0.3,0.1

Type RM Length L Ch R = 1 ,13910   ,440.3,451.7,447.5
XS GIS Cut Line= 4
2160230.87074754458902.2863289082160257.69120025459017.820586721
 2160321.6476644459176.6801912142160373.22545806  459401.5593716
#Sta/Elev= 30
       0  3210.2     7.1 3207.32    20.2 3204.69    39.9 3196.38    48.1 3194.14
    76.8 3182.64    93.5  3174.8   103.5 3166.13   113.8 3155.84   139.5 3133.55
  145.683129.226   153.8  3126.7   168.1 3126.38   191.2 3126.65  208.253129.227
   218.4 3130.26   251.6 3130.16   268.8  3133.3   281.8 3134.14   319.1 3134.62
   384.8 3133.03   413.5  3133.5   417.6  3134.5     434  3143.2   462.6 3161.38
     475 3167.62   483.3  3170.1   499.7 3178.51   507.9 3181.83   520.6 3190.03
#Mann= 5 ,-1,0
       0      .1       0  145.68    .045       0  208.25      .1       0
  288.61     .04       0  389.86      .1       0
#XS Ineff= 2 , 0
                          315.51         3137.12
Permanent Ineff=
       F       F
Bank Sta=145.68,208.25
XS Rating Curve= 0 ,0
Exp/Cntr(USF)=0,0
Exp/Cntr=0.3,0.1

Type RM Length L Ch R = 1 ,13458   ,443.6,390.3,362.3
XS GIS Cut Line= 4
2159809.99595123459116.8499505612159867.76308013459217.942426147
2159954.41377349 459426.31671256 2160008.0546789459533.598523387
#Sta/Elev= 30
       0 3174.21     9.6 3172.03    18.8 3167.66    48.7 3155.94    69.3 3144.77
    83.9 3135.26    89.8 3132.29   101.7 3129.33   115.6 3128.27   132.9 3128.07
  140.083123.631   141.6 3122.95   206.6 3123.26   215.2 3122.22   228.2 3121.88
   241.2 3122.09  247.043123.631   258.6 3127.32   275.3 3127.94   284.4 3130.48
   301.9 3130.19   310.5 3131.15   333.4 3130.99   340.9 3132.25   360.5 3140.07
   393.3  3157.8   403.4 3159.89   426.5 3171.96   443.7  3177.1   462.1 3184.32
#Mann= 4 ,-1,0
       0      .1       0  140.08    .045       0  247.04     .04       0
  382.11      .1       0
#XS Ineff= 2 , 0
                          261.83         3130.71
Permanent Ineff=
       F       F
Bank Sta=140.08,247.04
XS Rating Curve= 0 ,0
Exp/Cntr(USF)=0,0
Exp/Cntr=0.3,0.1

Type RM Length L Ch R = 1 ,13068   ,325.1,306.9,290.6
XS GIS Cut Line= 5
2159467.51940128459477.8945062272159554.17009464459521.219852907
2159721.28214612459595.4918757862159797.61728074459628.501663733
2159917.27776205459651.195892946
#Sta/Elev= 30
       0 3202.48     9.7 3199.89    14.1 3198.02    36.5 3183.65    54.4 3175.16
    89.4 3152.11   128.7 3122.29  141.813119.302   147.2 3117.21   160.4 3115.73
   173.5 3115.32   199.7 3116.23   204.1 3116.82  212.453119.304   230.4 3125.89
   247.9 3127.47   289.3 3127.45   301.5 3128.26   322.1 3126.63   335.2 3126.99
   361.3 3126.31   373.7 3127.33   381.8 3129.74   396.5 3135.39   414.4 3143.94
   422.5 3146.12   438.8 3154.18   459.2 3161.24   468.4 3163.73   484.7 3170.42
#Mann= 5 ,-1,0
       0      .1       0  141.81    .045       0  212.45      .1       0
  236.88     .04       0  452.92      .1       0
Bank Sta=141.81,212.45
XS Rating Curve= 0 ,0
Exp/Cntr(USF)=0,0
Exp/Cntr=0.3,0.1

Type RM Length L Ch R = 1 ,12761   ,360.2,358.4,356.8
XS GIS Cut Line= 4
2159432.44650159459845.1283971322159519.09719495459855.443955866
 2159764.6074928459863.6964028522159902.83597982459841.002173639
#Sta/Elev= 30
       0 3174.84    11.8 3170.53    27.9 3165.64    48.1 3158.24      61 3151.89
    68.2 3148.84    76.3 3143.19    80.3  3140.9    96.3 3135.74   100.3 3132.75
   104.3 3128.54   108.4 3125.07  120.843117.815   128.4  3115.3   140.3 3114.75
   172.4 3114.98  188.113117.813   204.4  3120.5   228.4 3121.37   244.4 3121.26
   276.4 3123.31   296.5 3122.46   332.9 3121.96   364.9 3122.98   376.5  3124.4
   381.1 3125.37   397.8 3130.69   421.7 3136.96   458.1 3151.32     473 3156.67
#Mann= 8 ,-1,0
       0      .1       0      60     .12       0  120.84    .045       0
  188.11      .1       0  257.26     .04       0  352.91      .1       0
  382.91     .04       0  452.91      .1       0
#XS Ineff= 2 , 0
                          277.23          3125.7
Permanent Ineff=
       F       F
Bank Sta=120.84,188.11
XS Rating Curve= 0 ,0
Exp/Cntr(USF)=0,0
Exp/Cntr=0.3,0.1

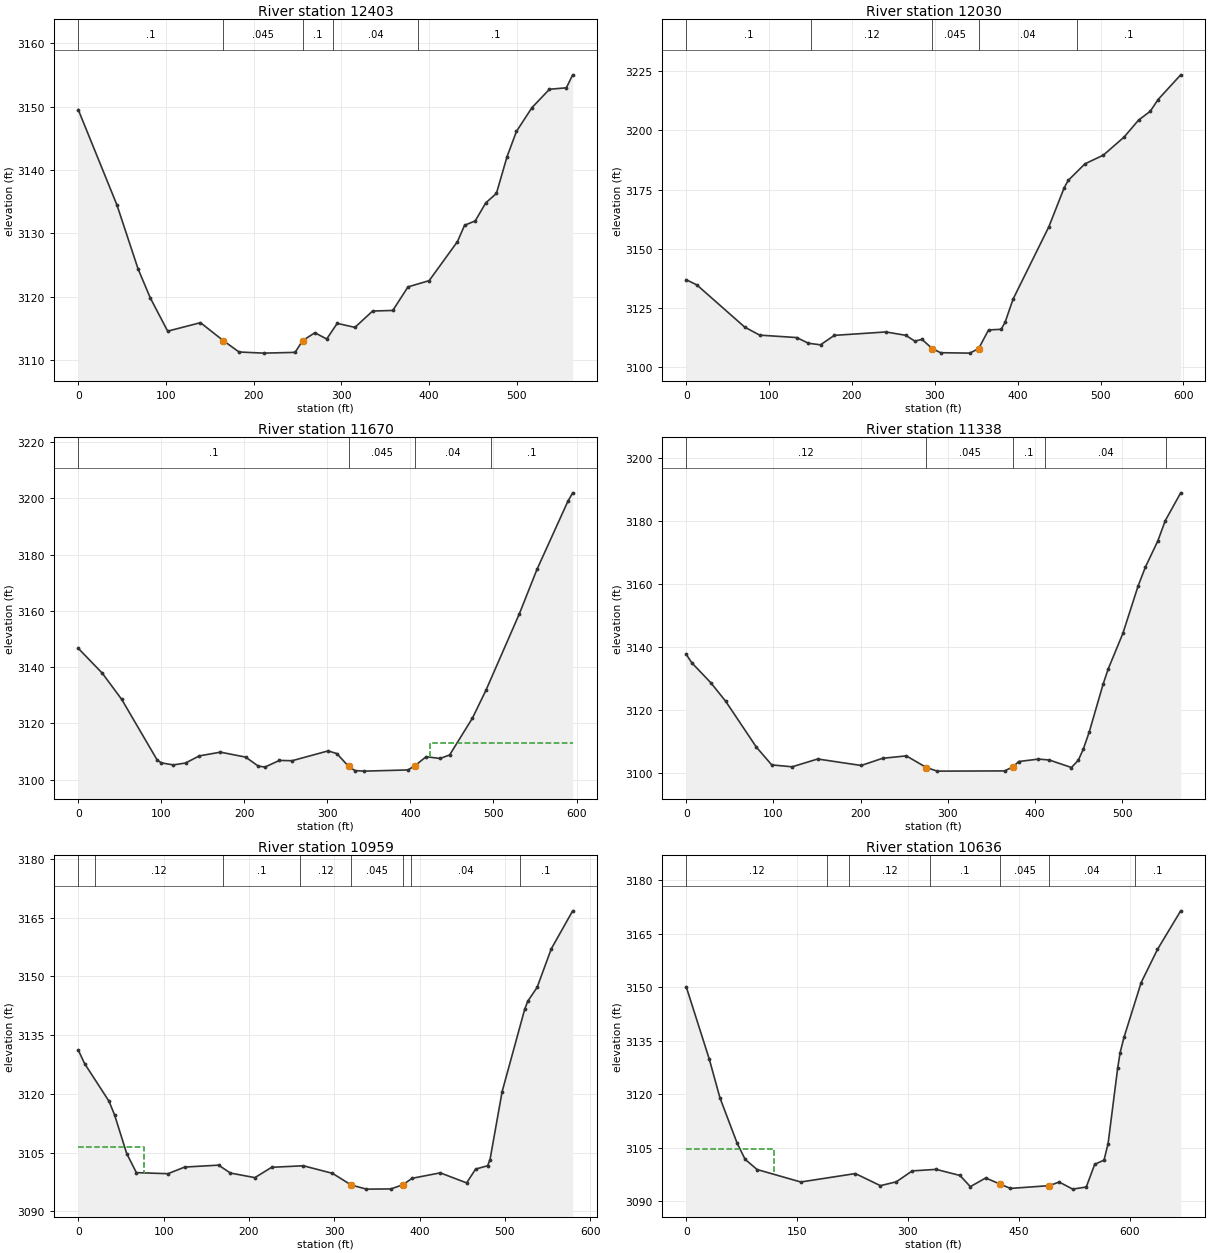
Type RM Length L Ch R = 1 ,12403   ,340.5,372.7,391
XS GIS Cut Line= 4
2159399.43671364460175.2262765982159523.22341844460216.488511531
2159690.33546992460214.4253997852159954.41377349460179.352500091
#Sta/Elev= 30
       0 3149.52    44.1 3134.48    68.2 3124.39    82.1 3119.81     102 3114.54
   139.4 3115.88  165.613113.031   183.4 3111.25   211.4 3111.07   247.4 3111.19
  255.833113.031   269.9 3114.29   283.4  3113.3   295.4 3115.77   315.6 3115.14
   335.8 3117.72   358.8 3117.81   376.1 3121.53   400.3 3122.52   432.6  3128.7
   440.7 3131.27   452.8 3131.95   464.9 3134.81     477  3136.3   489.1 3142.09
   499.8 3146.08   517.6 3149.86   537.5 3152.75   556.8 3152.98     564 3155.03
#Mann= 5 ,-1,0
       0      .1       0  165.61    .045       0  255.83      .1       0
  290.48     .04       0  387.61      .1       0
Bank Sta=165.61,255.83
XS Rating Curve= 0 ,0
Exp/Cntr(USF)=0,0
Exp/Cntr=0.3,0.1

Type RM Length L Ch R = 1 ,12030   ,349.6,360.4,369.2
XS GIS Cut Line= 4
2159306.59668504460350.5907750642159479.89807176460503.261044317
2159638.75767625460608.4797433972159787.30172201460701.319771997
#Sta/Elev= 30
       0 3136.92    12.8 3134.74    70.5 3116.94    88.6 3113.54   133.3 3112.51
   147.5  3110.1     162 3109.46   178.7 3113.44   240.9 3114.88   264.9 3113.46
   275.8 3111.01   284.5 3111.75  296.843107.854   306.9 3106.12   342.2 3105.94
  352.843107.853   364.8 3115.73     380    3116   384.8 3118.99   394.4 3128.75
   437.6 3159.31   456.2 3175.86   460.9 3178.85   481.1 3185.86   503.4 3189.55
   528.5 3197.21   545.8 3204.32     560 3208.08   569.4 3213.01   596.7 3223.45
#Mann= 5 ,-1,0
       0      .1       0     150     .12       0  296.84    .045       0
  352.84     .04       0   471.5      .1       0
Bank Sta=296.84,352.84
XS Rating Curve= 0 ,0
Exp/Cntr(USF)=0,0
Exp/Cntr=0.3,0.1

Type RM Length L Ch R = 1 ,11670   ,337.3,331.4,327.3
XS GIS Cut Line= 4
2159069.33883417460614.6690786372159296.28112631 460792.09668885
2159436.57272508460932.3882876232159523.22341844460998.407863516
#Sta/Elev= 30
       0 3146.71      29 3137.84    52.3 3128.56      95 3107.03   100.1 3105.99
   114.5 3105.27   129.2 3105.95   145.8 3108.48   171.2  3109.8   201.6 3108.04
   216.9 3104.82   224.9 3104.52   242.2 3106.86   257.5 3106.76   300.9 3110.25
   311.4 3109.29   325.5 3104.76   333.2 3103.25   344.5 3103.06   397.1 3103.48
  405.653105.022   418.9 3108.19   435.8 3107.56   447.2 3108.81   474.6 3121.86
     491 3131.83   531.2 3158.99   552.4 3174.75   589.5 3198.88   595.4 3201.96
#Mann= 4 ,-1,0
       0      .1       0   325.5    .045       0  405.65     .04       0
  496.47      .1       0
#XS Ineff= 2 , 0
                           423.1         3112.91
Permanent Ineff=
       F       F
Bank Sta=325.5,405.65
XS Rating Curve= 0 ,0
Exp/Cntr(USF)=0,0
Exp/Cntr=0.3,0.1

Type RM Length L Ch R = 1 ,11338   ,375,379.4,376.7
XS GIS Cut Line= 4
2158879.53255348 460866.368711732159063.14949893461037.606986702
2159215.81976819461165.5199149952159298.34423805461248.044384862
#Sta/Elev= 30
       0 3137.56     6.3 3134.92    28.2 3128.56    45.2  3122.7    80.4 3108.15
      98 3102.52   121.4 3101.91   150.7 3104.39   200.6 3102.33   225.1 3104.61
   252.4 3105.38   275.3 3101.69   287.8 3100.54   365.1 3100.61     375 3101.96
   381.2 3103.58   403.7 3104.35   416.2 3104.08   441.7 3101.69   449.7 3104.04
   455.4  3107.6   462.1 3112.94     478  3128.1   483.7 3132.84   500.7 3144.24
   518.1 3159.23   526.6 3165.33   540.8 3173.59   549.3    3180     567 3188.83
#Mann= 5 ,-1,0
       0     .12       0   275.3    .045       0     375      .1       0
  411.07     .04       0  550.25      .1       0
Bank Sta=275.3,375
XS Rating Curve= 0 ,0
Exp/Cntr(USF)=0,0
Exp/Cntr=0.3,0.1

Type RM Length L Ch R = 1 ,10959   ,320.6,323.2,324.1
XS GIS Cut Line= 4
2158601.01246768461124.257680062 2158805.2605306461301.685290275
2158920.79478841461392.4622071282159038.39215797461503.870241448
#Sta/Elev= 30
       0 3131.19     7.5 3127.71      36 3118.13    42.6  3114.6    56.8 3104.74
    68.1 3099.87   105.1 3099.59   124.8 3101.29   164.5 3101.78   178.3 3099.76
     207 3098.59   226.7 3101.23   263.8 3101.62   297.9 3099.69     320  3096.7
   337.8 3095.65   366.3  3095.7   380.5 3096.77   391.3 3098.42   424.3 3099.81
   455.2 3097.24   465.7 3100.77   479.8 3101.63   482.6 3103.18   496.8 3120.57
   523.2 3141.57   526.8 3143.67   537.8 3147.21   554.4 3157.06   579.5 3166.78
#Mann= 8 ,-1,0
       0      .1       0      20     .12       0     170      .1       0
     260     .12       0     320    .045       0   380.5      .1       0
  390.55     .04       0  517.48      .1       0
#XS Ineff= 2 , 0
            76.5 3106.47
Permanent Ineff=
       F       F
Bank Sta=320,380.5
XS Rating Curve= 0 ,0
Exp/Cntr(USF)=0,0
Exp/Cntr=0.3,0.1

Type RM Length L Ch R = 1 ,10636   ,451.9,449.9,446.8
XS GIS Cut Line= 4
 2158341.0603876461307.8746255152158615.45424991461555.448035114
2158757.80896043461677.1716281672158840.33343029461753.506762794
#Sta/Elev= 30
       0 3150.06    31.1 3129.84    45.6 3118.95    68.8 3106.28    79.6 3101.75
    95.8 3098.87     155 3095.37   228.9 3097.73   262.8 3094.34   284.3 3095.42
   305.9 3098.48   338.2 3098.91   370.5  3097.2   384.5 3094.07   405.4  3096.5
   425.2 3094.74   438.9 3093.57   491.6 3094.35   504.7 3095.37   523.1 3093.37
   541.5 3093.97   552.9 3100.33   565.5  3101.5     571 3106.11     584 3127.31
   587.3 3131.62   592.5 3135.88   615.8 3151.28   637.8 3160.54   669.3 3171.38
#Mann= 7 ,-1,0
       0     .12       0     190      .1       0     220     .12       0
     330      .1       0   425.2    .045       0   491.6     .04       0
  606.87      .1       0
#XS Ineff= 2 , 0
          118.28 3104.63
Permanent Ineff=
       F       F
Bank Sta=425.2,491.6
XS Rating Curve= 0 ,0
Exp/Cntr(USF)=0,0
Exp/Cntr=0.3,0.1

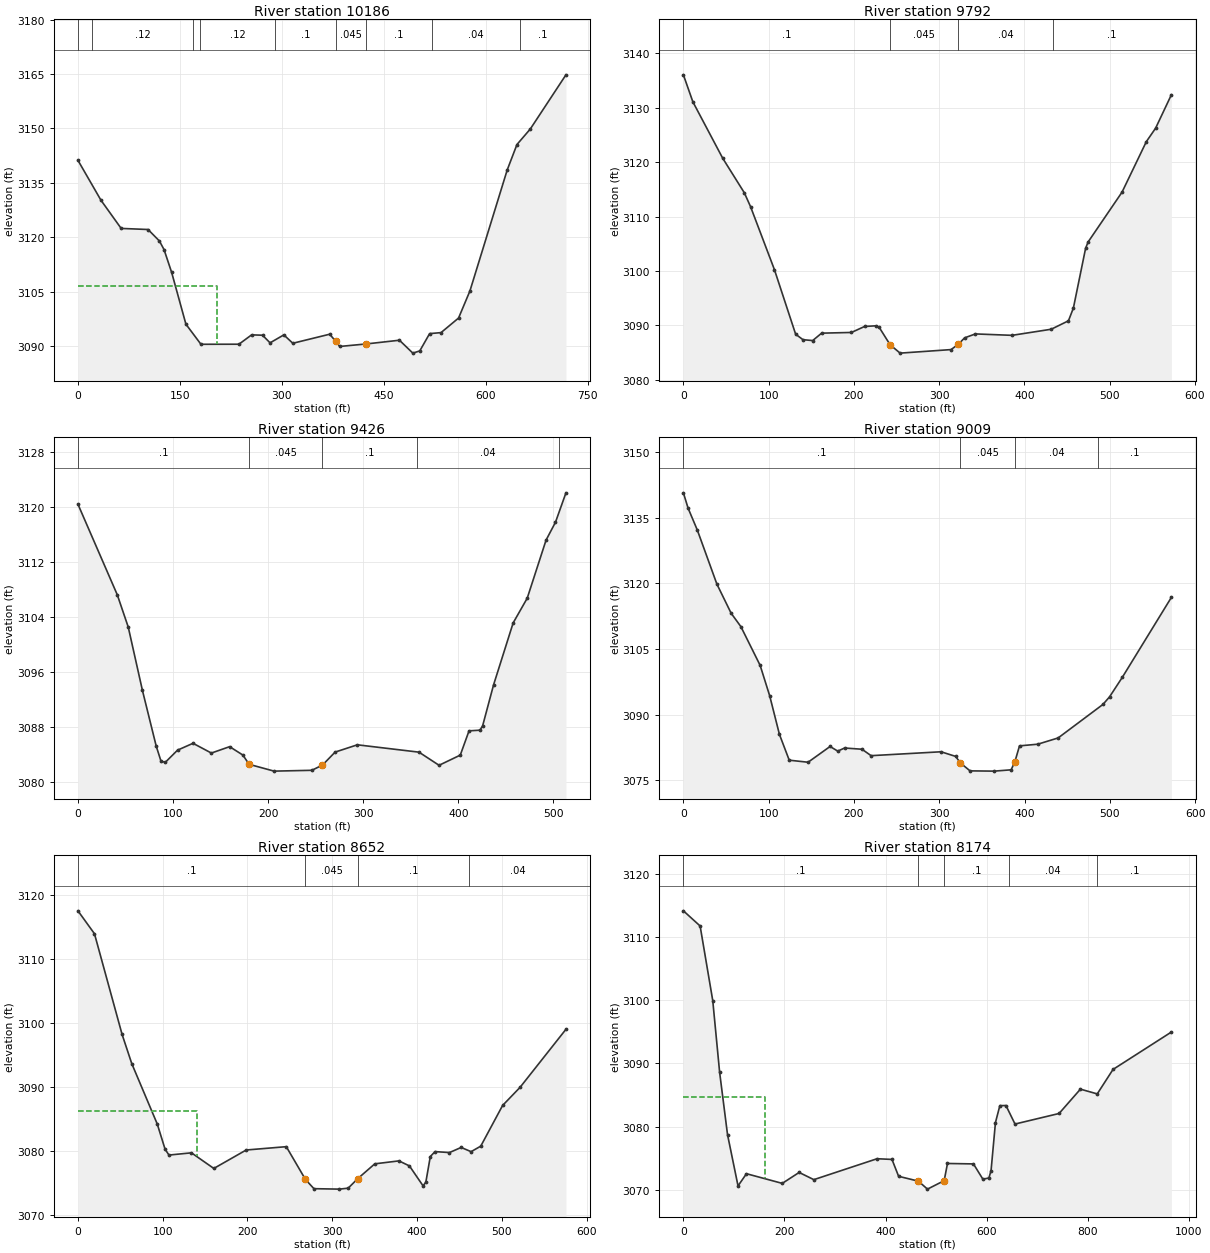
Type RM Length L Ch R = 1 ,10186   ,391.4,393.8,393.3
XS GIS Cut Line= 4
2158072.85586054  461718.43386312158363.75461682461930.934373006
 2158438.0266397461982.5121666732158654.65337309462139.308659419
#Sta/Elev= 30
       0 3141.22    33.8 3130.23    63.6 3122.43   103.2 3122.13   119.9 3118.96
   126.7 3116.59   137.9 3110.29   158.9 3096.01     181 3090.47   236.9 3090.49
   255.6 3093.07   271.6 3092.97   282.7 3090.87     303 3093.06   316.2 3090.75
   370.5 3093.25   379.4 3091.26   385.2 3089.87   424.1 3090.56   473.1 3091.59
   492.8 3088.03     503 3088.64   517.5 3093.41   534.3 3093.69   560.1 3097.71
   576.8 3105.18   631.7 3138.57     646 3145.57   665.7 3149.87   718.1  3164.8
#Mann= 9 ,-1,0
       0      .1       0      20     .12       0     170      .1       0
     180     .12       0     290      .1       0   379.4    .045       0
   424.1      .1       0  520.67     .04       0  650.67      .1       0
#XS Ineff= 2 , 0
          203.99 3106.65
Permanent Ineff=
       F       F
Bank Sta=379.4,424.1
XS Rating Curve= 0 ,0
Exp/Cntr(USF)=0,0
Exp/Cntr=0.3,0.1

Type RM Length L Ch R = 1 ,9792    ,372.8,366.6,359.8
XS GIS Cut Line= 4
2157959.38471447462073.2890835262158126.49676595462201.202011819
2158246.15724726462296.1051521652158419.45863398462413.702521725
#Sta/Elev= 30
       0 3136.06    11.1  3131.1    46.1 3120.74    71.5 3114.38    78.8 3111.83
   106.8 3100.26   131.7 3088.39   140.3 3087.38   151.7 3087.22   162.2 3088.58
   197.2 3088.71   212.6 3089.81   225.9 3089.93   229.7 3089.66   242.6 3086.44
   254.3 3084.91   314.1 3085.56   322.7 3086.56     330 3087.72   342.6 3088.44
   385.6 3088.18   431.6  3089.3   451.8 3090.85   457.6 3093.19   471.9 3104.15
   474.8 3105.32   514.7  3114.5   543.2 3123.78   554.1 3126.26   572.6  3132.4
#Mann= 4 ,-1,0
       0      .1       0   242.6    .045       0   322.7     .04       0
  433.17      .1       0
Bank Sta=242.6,322.7
XS Rating Curve= 0 ,0
Exp/Cntr(USF)=0,0
Exp/Cntr=0.3,0.1

Type RM Length L Ch R = 1 ,9426    ,407,416.5,431
XS GIS Cut Line= 4
  2157784.020216462419.891856965 2157911.9331443462506.542550325
2158033.65673735462578.7514614582158209.02123582462706.664389751
#Sta/Elev= 30
       0 3120.37    41.4 3107.18    52.9 3102.49    67.8 3093.28    82.3 3085.17
    87.4 3082.95      92 3082.83   104.7 3084.58     121 3085.58   140.3 3084.16
   159.5 3085.09   173.4 3083.87     180 3082.52   206.2 3081.53   245.9 3081.65
   257.1 3082.41   270.4  3084.3   293.8 3085.36   358.6 3084.29   379.7 3082.38
     402 3083.86   411.2 3087.39   422.7 3087.49   425.5 3088.12     437 3094.08
   457.6  3103.1   472.4  3106.7   492.2 3115.15   502.1 3117.75   513.1 3122.03
#Mann= 5 ,-1,0
       0      .1       0     180    .045       0   257.1      .1       0
  356.03     .04       0  506.03      .1       0
Bank Sta=180,257.1
XS Rating Curve= 0 ,0
Exp/Cntr(USF)=0,0
Exp/Cntr=0.3,0.1

Type RM Length L Ch R = 1 ,9009    ,354.4,357.5,361.3
XS GIS Cut Line= 4
2157548.82547688462661.2759313242157755.13665155462869.650217737
 2157850.0397919462976.9320285632157949.06915574463069.772057163
#Sta/Elev= 30
       0  3140.7     5.5  3137.2    16.4 3132.16    39.3 3119.84      56 3113.19
    67.4 3110.14      90 3101.28   101.2 3094.33   112.6 3085.53   124.1 3079.63
   146.2 3079.16     172 3082.76     181  3081.7     189 3082.41   209.4 3082.13
   220.1 3080.66   302.1 3081.55   319.3 3080.49   324.6 3079.03   336.1 3077.19
   364.5 3077.13   384.3 3077.43  388.743079.312   394.1  3082.9   415.5 3083.28
   439.4 3084.71   491.9 3092.36   499.7  3094.1   514.6 3098.54   572.2 3116.82
#Mann= 4 ,-1,0
       0      .1       0   324.6    .045       0  388.74     .04       0
  486.46      .1       0
Bank Sta=324.6,388.74
XS Rating Curve= 0 ,0
Exp/Cntr(USF)=0,0
Exp/Cntr=0.3,0.1

Type RM Length L Ch R = 1 ,8652    ,466.8,477,481.2
XS GIS Cut Line= 4
 2157354.8929727462875.8395529772157458.04856003463057.393386683
2157555.01481212463187.3694267232157689.11707566463342.102807723
#Sta/Elev= 30
       0 3117.55    19.5 3113.97    52.1 3098.24    63.5 3093.69    93.6 3084.25
   102.8 3080.32   107.4 3079.41   133.9 3079.76   160.3 3077.32   198.5  3080.2
   245.8 3080.72   268.4  3075.6   278.4 3074.16   308.4 3074.09   318.8 3074.24
   330.2 3075.74   350.2 3078.04   378.7  3078.5   391.1 3077.71   407.1 3074.61
   410.4 3075.16   415.7 3079.18   421.3 3079.95   438.3  3079.8   452.1  3080.6
   463.8 3079.94   475.2  3080.8     501 3087.16   521.6 3089.99   575.7 3099.05
#Mann= 4 ,-1,0
       0      .1       0   268.4    .045       0   330.2      .1       0
  460.97     .04       0
#XS Ineff= 2 , 0
          140.09 3086.36
Permanent Ineff=
       F       F
Bank Sta=268.4,330.2
XS Rating Curve= 0 ,0
Exp/Cntr(USF)=0,0
Exp/Cntr=0.3,0.1

Type RM Length L Ch R = 1 ,8174    ,89.2,103.3,115.1
XS GIS Cut Line= 4
2157030.98442847462993.4369225372157144.45557454463381.301930909
2157241.42182663463606.1811112952157507.56324195463777.419386268
#Sta/Elev= 30
       0 3114.14    33.1 3111.74    58.1 3099.93    71.7 3088.58    87.3 3078.73
   108.1 3070.61   124.8 3072.54   195.6 3071.01     229 3072.74   258.1  3071.6
   383.2 3074.91   412.7  3074.8   425.8 3072.13     465 3071.36   482.9  3070.1
  515.95 3071.44   522.5 3074.16   573.9 3074.09   592.5 3071.68   604.4 3071.86
   608.7 3073.02   617.4 3080.63   626.1 3083.31   638.2 3083.33   656.1  3080.4
   743.3 3082.07   785.5 3085.92   818.8 3085.17     850 3089.04   965.5 3094.96
#Mann= 5 ,-1,0
       0      .1       0     465    .045       0  515.95      .1       0
  644.12     .04       0  819.02      .1       0
#XS Ineff= 2 , 0
          161.29 3084.61
Permanent Ineff=
       F       F
Bank Sta=465,515.95
XS Rating Curve= 0 ,0
Exp/Cntr(USF)=0,0
Exp/Cntr=0.3,0.1