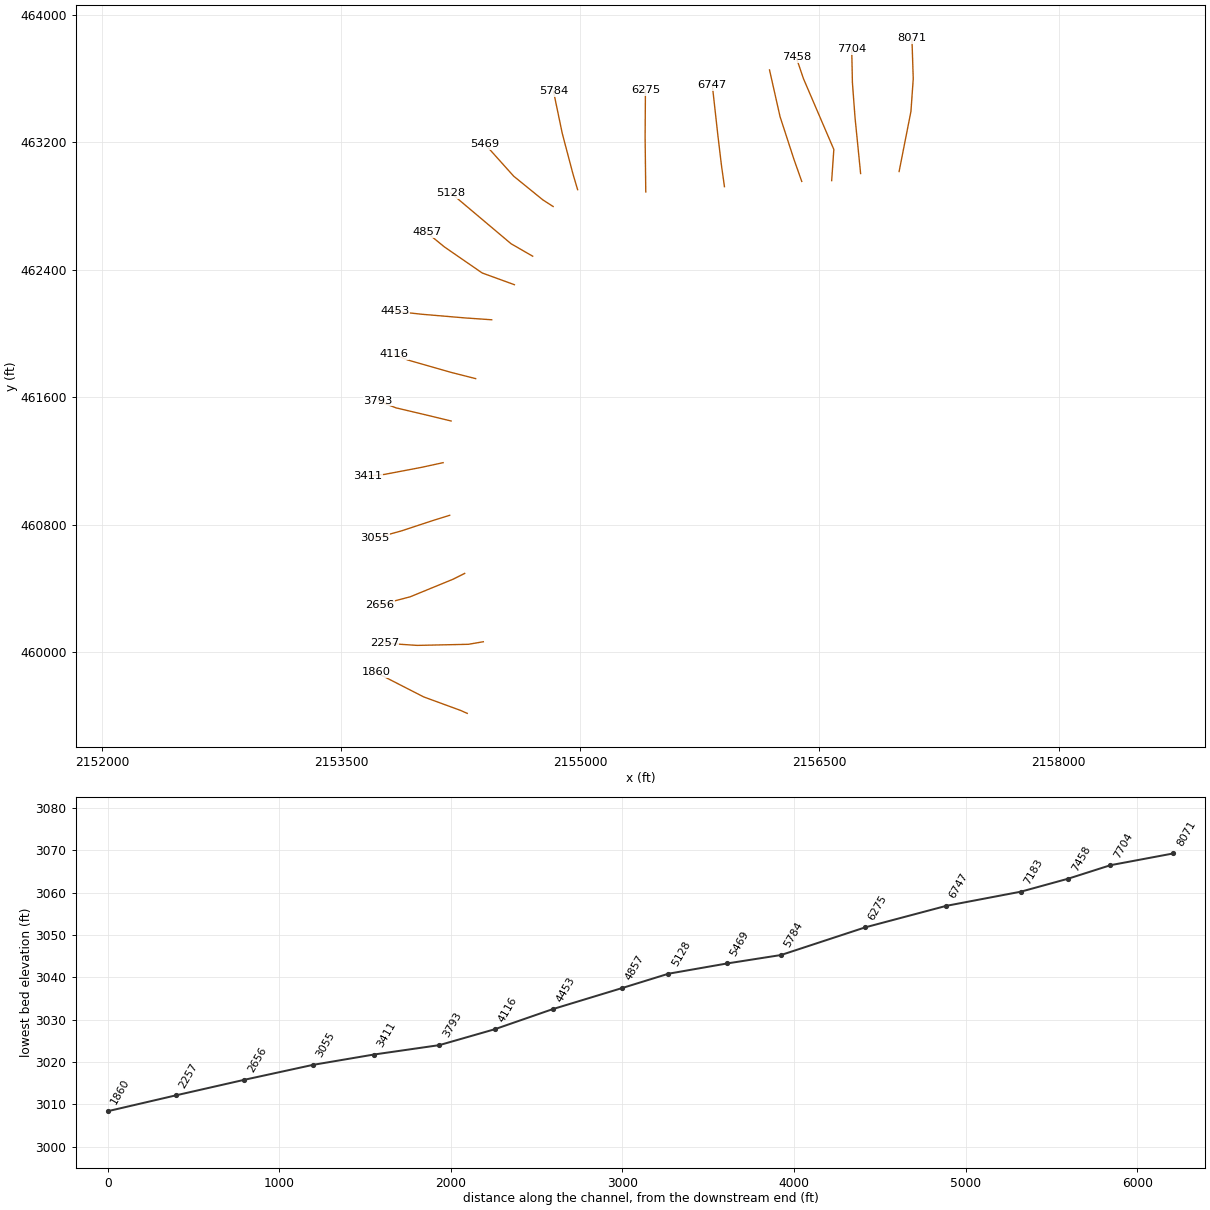
HEC-RAS study CRANBRYRV.prj: CRANBRYRV

--- CRANBRYRV.g01 (geometry) --- (continued)

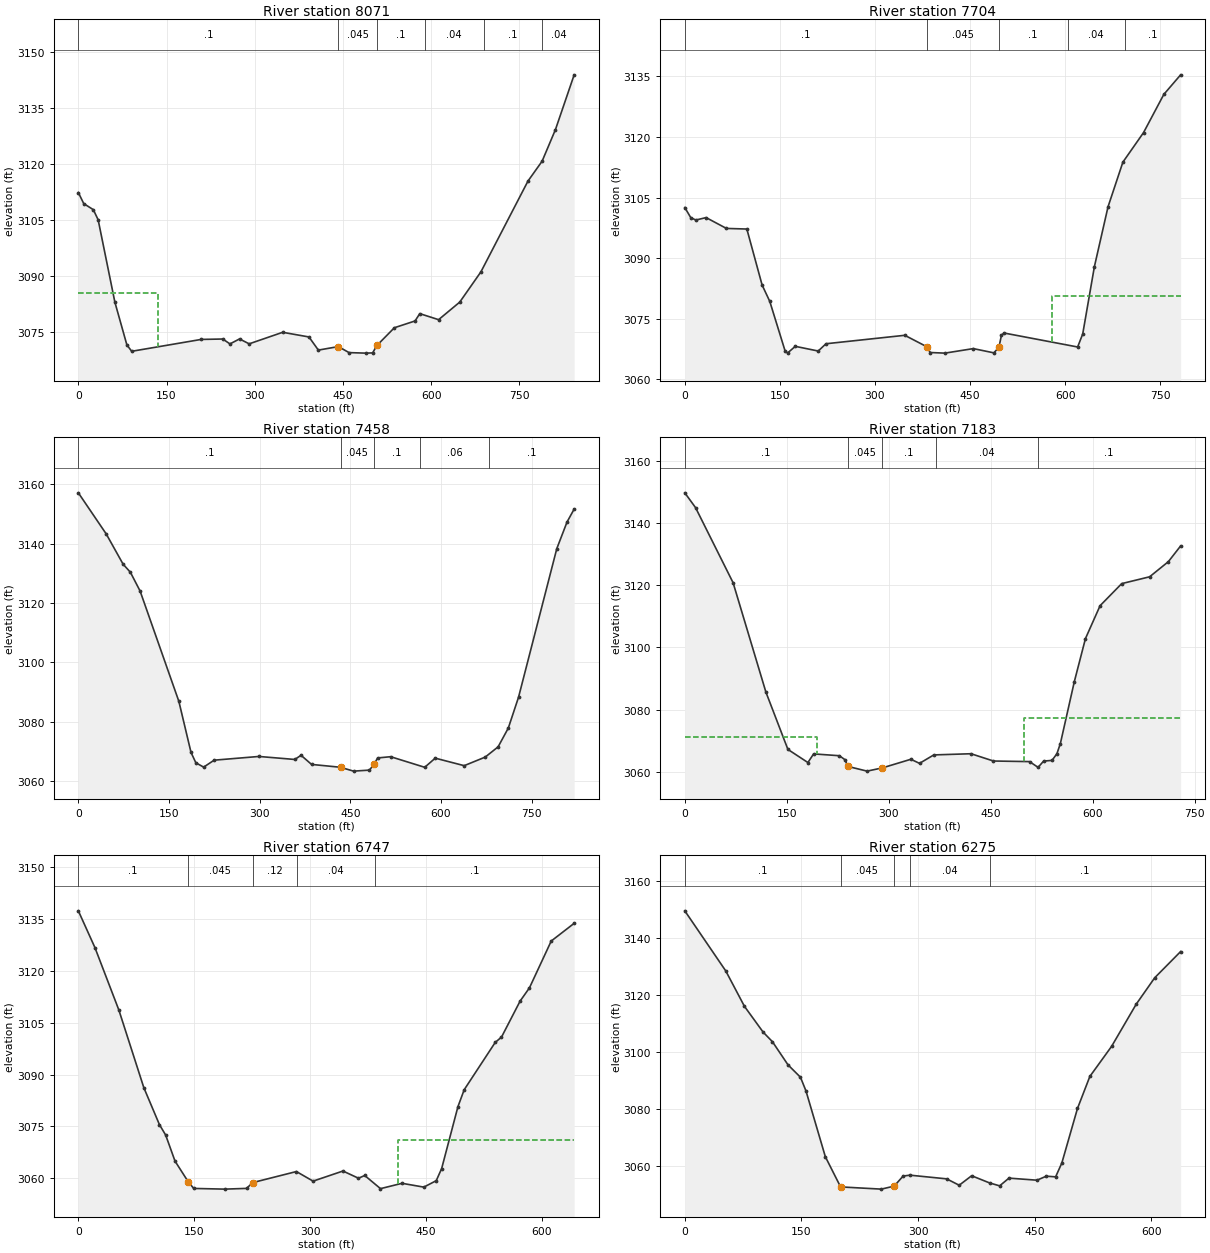
Type RM Length L Ch R = 1 ,8071    ,362.8,367.3,372.4
XS GIS Cut Line= 4
2157000.03775227 463016.131151752157074.30977515463393.680601389
2157088.75155738463597.9286643082157080.49911039463851.691409148
#Sta/Elev= 30
       0  3112.3     9.2 3109.34    25.5 3107.71    33.7 3105.01    62.2 3082.92
    82.6 3071.48    90.8 3069.78     209 3072.96   245.7 3073.07   257.9 3071.76
   274.2 3073.09   290.6 3071.78   347.6 3074.87   392.3 3073.62   408.3  3070.1
   442.2 3071.04   460.5 3069.43   488.5 3069.29   500.6 3069.35  507.833071.335
   537.6 3076.09   572.8 3077.91   580.8 3079.87   612.8 3078.25   648.8 3082.96
   684.8 3091.06   764.9 3115.39   788.9  3120.7   811.6 3129.17   843.4 3143.83
#Mann= 6 ,-1,0
       0      .1       0   442.2    .045       0  507.83      .1       0
  589.54     .04       0  689.54      .1       0  789.54     .04       0
#XS Ineff= 2 , 0
          135.18 3085.48
Permanent Ineff=
       F       F
Bank Sta=442.2,507.83
XS Rating Curve= 0 ,0
Exp/Cntr(USF)=0,0
Exp/Cntr=0.3,0.1

Type RM Length L Ch R = 1 ,7704    ,211.3,245.6,253.4
XS GIS Cut Line= 4
2156758.65367791 463003.752481272156723.58077822463354.481478202
2156707.07588425463575.2344350952156702.94966075463783.608721508
#Sta/Elev= 30
       0 3102.52     9.5    3100    17.5 3099.43    33.6 3100.03    65.7 3097.35
    97.9  3097.2     122 3083.34   134.1 3079.29   158.2 3067.06   162.2 3066.53
   174.3 3068.18   210.5 3067.02   222.8 3068.82   347.1 3070.91   382.1 3068.06
   387.3 3066.65   410.4  3066.5   455.2 3067.62   487.6 3066.57   495.6 3067.94
   499.6 3070.91   503.6 3071.48   619.8 3068.02   627.8 3071.22   646.3 3087.93
   667.8 3102.72   691.2 3113.75   723.8 3121.06   755.8 3130.51   782.3 3135.35
#Mann= 5 ,-1,0
       0      .1       0   382.1    .045       0   495.6      .1       0
  603.85     .04       0  693.85      .1       0
#XS Ineff= 2 , 0
                           578.8         3080.59
Permanent Ineff=
       F       F
Bank Sta=382.1,495.6
XS Rating Curve= 0 ,0
Exp/Cntr(USF)=0,0
Exp/Cntr=0.3,0.1

Type RM Length L Ch R = 1 ,7458    ,257.4,275.5,268.4
XS GIS Cut Line= 4
2156577.05541317462959.256500688 2156590.6511461463154.741360909
2156399.93697259  463599.05787912156354.77776621463732.306692604
#Sta/Elev= 30
       0 3157.07    46.1 3143.23    74.1 3133.02    86.1 3130.32   102.2 3123.97
   166.3 3086.82   186.4 3069.62   194.4 3066.13   207.3 3064.67   224.7 3067.01
   298.7 3068.26   358.1 3067.25   368.4 3068.66   385.8 3065.58   433.7 3064.62
   455.2 3063.32   481.5 3063.66     489 3065.56   495.1 3067.76   516.6 3068.18
     573 3064.61   590.4 3067.69   638.3 3065.16   673.1 3068.05   694.4  3071.5
   711.3 3077.84   728.2 3088.23   791.5 3138.28   808.4 3147.23   820.2  3151.6
#Mann= 5 ,-1,0
       0      .1       0   433.7    .045       0     489      .1       0
  565.96     .06       0  679.47      .1       0
Bank Sta=433.7,489
XS Rating Curve= 0 ,0
Exp/Cntr(USF)=0,0
Exp/Cntr=0.3,0.1

Type RM Length L Ch R = 1 ,7183    ,444.9,435.7,428.4
XS GIS Cut Line= 4
2156389.35667526 462954.237799352156339.84199334463094.529398123
2156253.19129998463360.6708134422156187.17172409463653.632681468
#Sta/Elev= 30
       0  3149.7    15.8 3144.95      71 3120.81   119.2 3085.68   151.6 3067.23
     181 3063.01   189.4 3065.79   227.3  3065.2   235.7 3063.89   239.5 3061.78
     268 3060.25   290.6  3061.3   332.4 3064.06   345.1 3062.75   366.1 3065.46
   420.8 3065.84   453.8  3063.5   506.9 3063.31   519.4 3061.46   527.6 3063.48
   539.9  3063.7   547.1 3065.83   552.2 3069.12   572.7    3089   589.1 3102.87
   610.6 3113.43   642.4 3120.52   683.4 3122.71     711 3127.58     729 3132.63
#Mann= 5 ,-1,0
       0      .1       0   239.5    .045       0   290.6      .1       0
  368.77     .04       0  518.67      .1       0
#XS Ineff= 2 , 0
          193.83 3071.06  498.92         3077.28
Permanent Ineff=
       F       F
Bank Sta=239.5,290.6
XS Rating Curve= 0 ,0
Exp/Cntr(USF)=0,0
Exp/Cntr=0.3,0.1

Type RM Length L Ch R = 1 ,6747    ,478.8,472.1,468.1
XS GIS Cut Line= 4
 2155904.5254148462921.2280114042155885.95740908 463053.26716319
2155863.26317986463243.0734438832155828.19028017463558.729541122
#Sta/Elev= 30
       0 3137.29    21.5 3126.66    52.5 3108.62    84.8 3086.21     105 3075.54
   113.1 3072.51   125.2 3064.99   142.1 3059.09   149.4 3057.09   189.6 3056.89
   217.8  3057.1   225.9 3058.78   282.4 3061.97     304  3059.2   342.7 3062.12
   362.8 3060.04   370.9 3060.83   391.3 3057.03   419.2 3058.57   447.4 3057.47
   463.5 3059.33   470.5 3062.83   491.6 3080.72   499.7 3085.61   539.9 3099.28
     548 3100.81   572.1 3111.21   584.2 3115.04   612.4 3128.56   642.1 3133.68
#Mann= 5 ,-1,0
       0      .1       0   142.1    .045       0   225.9     .12       0
  283.34     .04       0   384.5      .1       0
#XS Ineff= 2 , 0
                          413.98         3071.07
Permanent Ineff=
       F       F
Bank Sta=142.1,225.9
XS Rating Curve= 0 ,0
Exp/Cntr(USF)=0,0
Exp/Cntr=0.3,0.1

Type RM Length L Ch R = 1 ,6275    ,473.5,490.6,498.2
XS GIS Cut Line= 3
2155410.99382555462888.4540752732155406.86760206463230.930625219
 2155408.9307138463525.955604992
#Sta/Elev= 30
       0 3149.65    52.7 3128.51    76.7 3116.07   100.7 3107.01   112.7 3103.63
   132.7  3095.5   148.7 3091.15   155.8 3086.34   180.7 3063.21   200.3 3052.59
   252.7 3051.81   269.2 3052.87   280.7  3056.4   289.4 3056.72   336.7 3055.42
   352.8 3053.18   368.8 3056.51   391.8    3054   404.8 3052.96   416.8 3055.68
   452.8 3054.95   464.8 3056.36   476.8 3056.13   484.8 3061.02   504.9 3080.18
   520.8 3091.43   548.8 3102.02   580.4 3116.83   604.2 3126.12   637.5 3135.33
#Mann= 5 ,-1,0
       0      .1       0   200.3    .045       0   269.2     .12       0
   289.4     .04       0   391.8      .1       0
Bank Sta=200.3,269.2
XS Rating Curve= 0 ,0
Exp/Cntr(USF)=0,0
Exp/Cntr=0.3,0.1

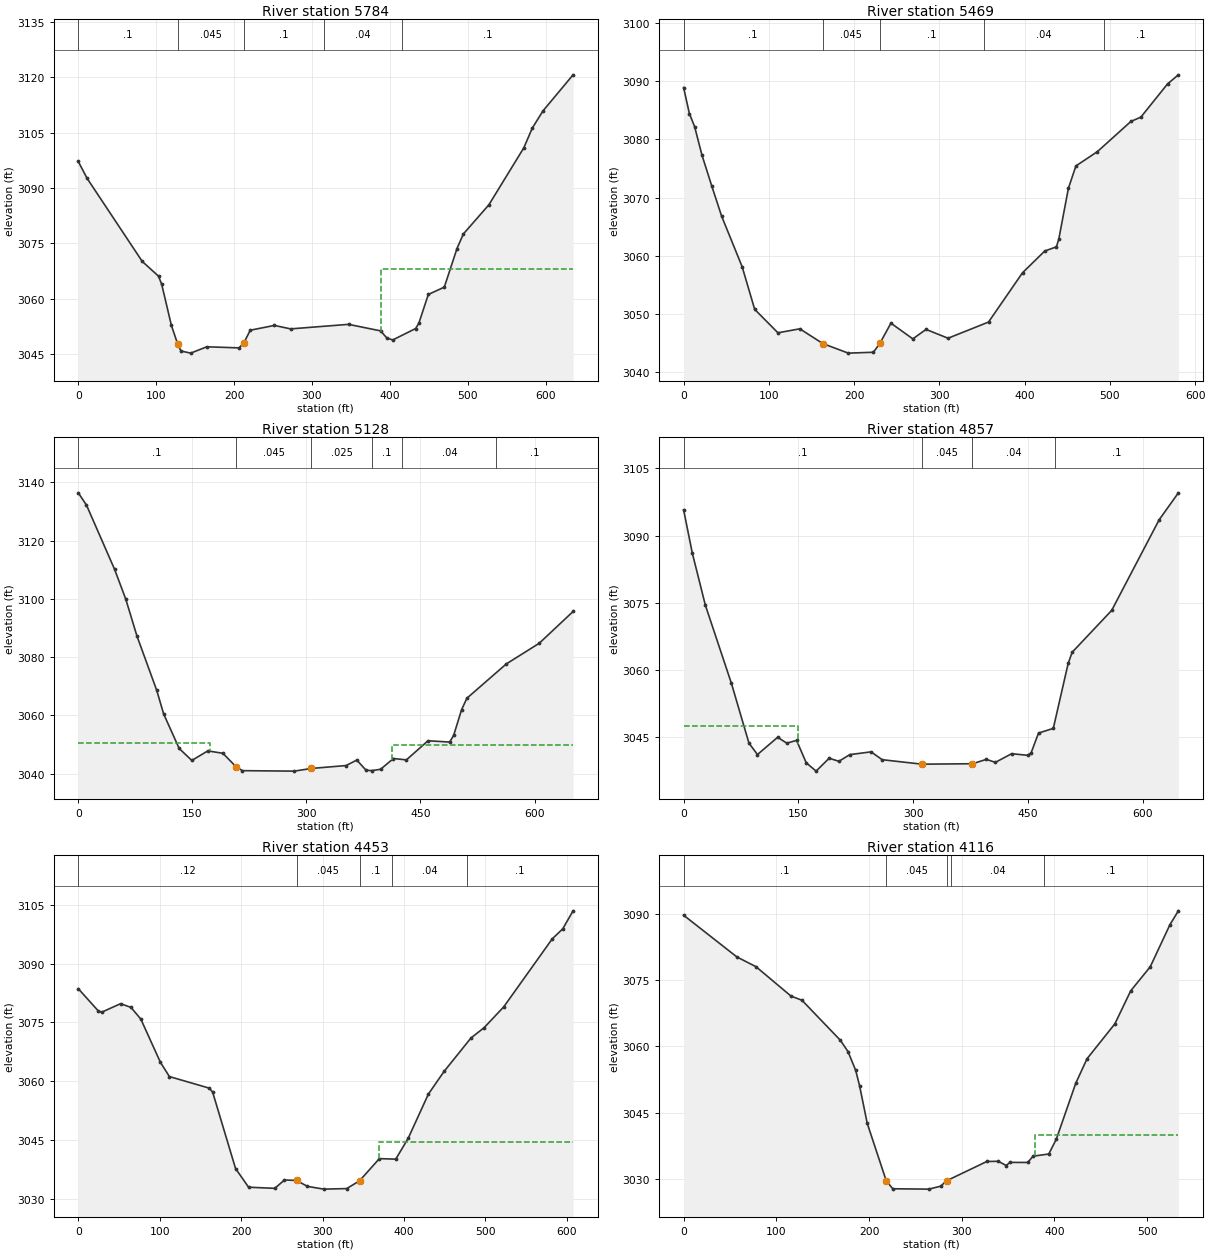
Type RM Length L Ch R = 1 ,5784    ,277.1,315.2,336.5
XS GIS Cut Line= 4
2154983.46063723462902.4307710452154953.66013422463003.294011993
2154887.18208905463255.4521143632154832.16577581463519.071948658
#Sta/Elev= 30
       0 3097.21    11.2 3092.68    82.1 3070.13     103 3066.13   107.1 3063.92
   119.5 3052.81   127.8 3047.61   131.9 3045.84   144.4 3045.27     165 3046.99
   206.4 3046.69   212.7  3048.1   220.8 3051.48   251.8 3052.78   272.6 3051.84
     347 3053.07   388.1  3051.3   396.3 3049.33   403.8 3048.85   433.1 3051.94
   437.2 3053.37   449.4 3061.18   469.9 3063.15   486.2 3073.62   494.4 3077.58
   527.1 3085.46     572 3100.92   582.9 3106.28   596.5  3110.9   635.2  3120.7
#Mann= 5 ,-1,0
       0      .1       0   127.8    .045       0   212.7      .1       0
  315.17     .04       0  415.95      .1       0
#XS Ineff= 2 , 0
                          389.25         3067.94
Permanent Ineff=
       F       F
Bank Sta=127.8,212.7
XS Rating Curve= 0 ,0
Exp/Cntr(USF)=0,0
Exp/Cntr=0.3,0.1

Type RM Length L Ch R = 1 ,5469    ,344,340.8,337.7
XS GIS Cut Line= 4
2154829.87342942462796.9828373272154765.68773064 462838.24507226
2154582.30001983462987.2475872972154403.49700178463186.681722807
#Sta/Elev= 30
       0 3088.91     6.8 3084.43    12.9 3082.21    21.6 3077.27    33.2 3071.92
    44.7 3066.77    68.6 3058.15    83.4 3050.79   110.7 3046.76   136.3 3047.45
   163.4 3044.91   193.2 3043.27   222.6 3043.42   230.2 3044.93   243.2 3048.42
   268.9 3045.72   284.4 3047.35   310.2 3045.83   357.7 3048.61   397.6 3057.09
   423.6 3060.81   437.3 3061.54   440.1 3062.85   451.4  3071.6   460.2 3075.44
   485.4  3077.9   524.7 3083.09   536.4 3083.83   567.7 3089.54   580.4  3091.1
#Mann= 5 ,-1,0
       0      .1       0   163.4    .045       0   230.2      .1       0
  352.59     .04       0  492.59      .1       0
Bank Sta=163.4,230.2
XS Rating Curve= 0 ,0
Exp/Cntr(USF)=0,0
Exp/Cntr=0.3,0.1

Type RM Length L Ch R = 1 ,5128    ,273.9,271.2,275.7
XS GIS Cut Line= 4
2154701.50203185462485.2237289432154566.25359513462563.163506039
2154318.68018553 462771.767027092154188.01644157462881.799653579
#Sta/Elev= 30
       0 3136.39    10.8 3132.17    47.7 3110.15    62.4 3099.94    77.1 3087.28
   103.1 3068.62   112.3 3060.46   132.7 3048.62   149.3 3044.52   170.4  3047.8
   190.2 3046.97   207.3  3042.4   215.8 3041.01   283.9 3040.85   306.6 3041.77
   352.3 3042.77   366.2 3044.65   378.5 3041.15   386.1 3041.03   397.5 3041.49
   414.5 3045.18   431.5 3044.71   459.9 3051.28   488.3 3050.82   493.6 3053.09
     504 3061.89     511 3065.86   562.8 3077.64   606.2 3084.75650.6613 3095.65
#Mann= 6 ,-1,0
       0      .1       0   207.3    .045       0   306.6    .025       0
   386.1      .1       0   426.1     .04       0  549.84      .1       0
#XS Ineff= 2 , 0
          173.27 3050.61  411.99          3049.7
Permanent Ineff=
       F       F
Bank Sta=207.3,306.6
XS Rating Curve= 0 ,0
Exp/Cntr(USF)=0,0
Exp/Cntr=0.3,0.1

Type RM Length L Ch R = 1 ,4857    ,381.8,404.1,426.9
XS GIS Cut Line= 4
 2154586.8847126462306.420710899 2154385.1582307462379.775795224
2154149.04655303462542.5323885722154036.72158015462634.226243979
#Sta/Elev= 30
       0 3095.74    11.4 3086.06    28.4 3074.48    62.5 3057.01    85.4 3043.69
    96.5 3041.15   122.9    3045   134.8 3043.69   147.6  3044.3   160.2 3039.31
   173.1 3037.45   190.2 3040.33   202.9 3039.64   217.1 3041.13     245 3041.75
   259.4    3040   311.3    3039   377.4  3039.1   395.6 3040.07   407.4 3039.41
   428.6 3041.34   449.3 3040.98   453.9 3041.47   463.7 3045.94     483 3046.98
   502.5 3061.52   507.7 3063.97   559.3  3073.3   621.3 3093.51646.4211 3099.52
#Mann= 4 ,-1,0
       0      .1       0   311.3    .045       0   377.4     .04       0
  484.65      .1       0
#XS Ineff= 2 , 0
          149.39  3047.5
Permanent Ineff=
       F       F
Bank Sta=311.3,377.4
XS Rating Curve= 0 ,0
Exp/Cntr(USF)=0,0
Exp/Cntr=0.3,0.1

Type RM Length L Ch R = 1 ,4453    ,345,337.5,328.8
XS GIS Cut Line= 4
2154444.75923671462086.3554579222154279.71029698462097.817189847
2154009.21342353462120.7406536992153839.57979103462139.079424781
#Sta/Elev= 30
       0  3083.6    24.6 3077.92    28.7  3077.6    51.9 3079.77    64.7 3078.83
    76.8 3075.84   100.8 3064.84   111.9 3061.18     161 3058.22     165  3057.2
   193.1 3037.73   209.1 3032.96   241.3 3032.67   253.2 3034.81     268 3034.68
   281.4 3033.17   301.4 3032.47   329.6 3032.61  345.333034.587   369.7 3040.25
   389.8 3040.12     405  3045.4   429.9 3056.72   449.1 3062.48   482.2 3071.03
   498.3 3073.65   522.4 3078.96   581.9 3096.29   594.9 3098.88 607.535 3103.46
#Mann= 5 ,-1,0
       0     .12       0     268    .045       0  345.33      .1       0
  385.45     .04       0  476.91      .1       0
#XS Ineff= 2 , 0
                          368.87         3044.42
Permanent Ineff=
       F       F
Bank Sta=268,345.33
XS Rating Curve= 0 ,0
Exp/Cntr(USF)=0,0
Exp/Cntr=0.3,0.1

Type RM Length L Ch R = 1 ,4116    ,322.9,322.4,323.5
XS GIS Cut Line= 4
2154343.89599577461717.2876899082154190.30878796461756.257578456
2153917.51956812461834.1973555522153832.70275187 461868.58255133
#Sta/Elev= 30
       0 3089.64    57.5  3080.2    78.1    3078   115.9 3071.35   127.6 3070.43
     169 3061.39   177.3 3058.83   185.6 3054.58   189.8  3051.1   198.1 3042.57
  218.553029.621   225.6  3027.8   264.5 3027.72   277.2 3028.38  283.78 3029.62
   327.1 3033.97   339.6 3034.01   347.9 3033.06     352 3033.76   371.2 3033.75
     377 3035.17   393.9 3035.66     402 3039.01     423 3051.66   435.2 3057.21
   465.2 3065.09   482.3 3072.56   503.3 3077.97   524.6 3087.51533.6809 3090.63
#Mann= 5 ,-1,0
       0      .1       0  218.55    .045       0  283.78      .1       0
  288.45     .04       0  388.45      .1       0
#XS Ineff= 2 , 0
                          378.88         3039.88
Permanent Ineff=
       F       F
Bank Sta=218.55,283.78
XS Rating Curve= 0 ,0
Exp/Cntr(USF)=0,0
Exp/Cntr=0.3,0.1

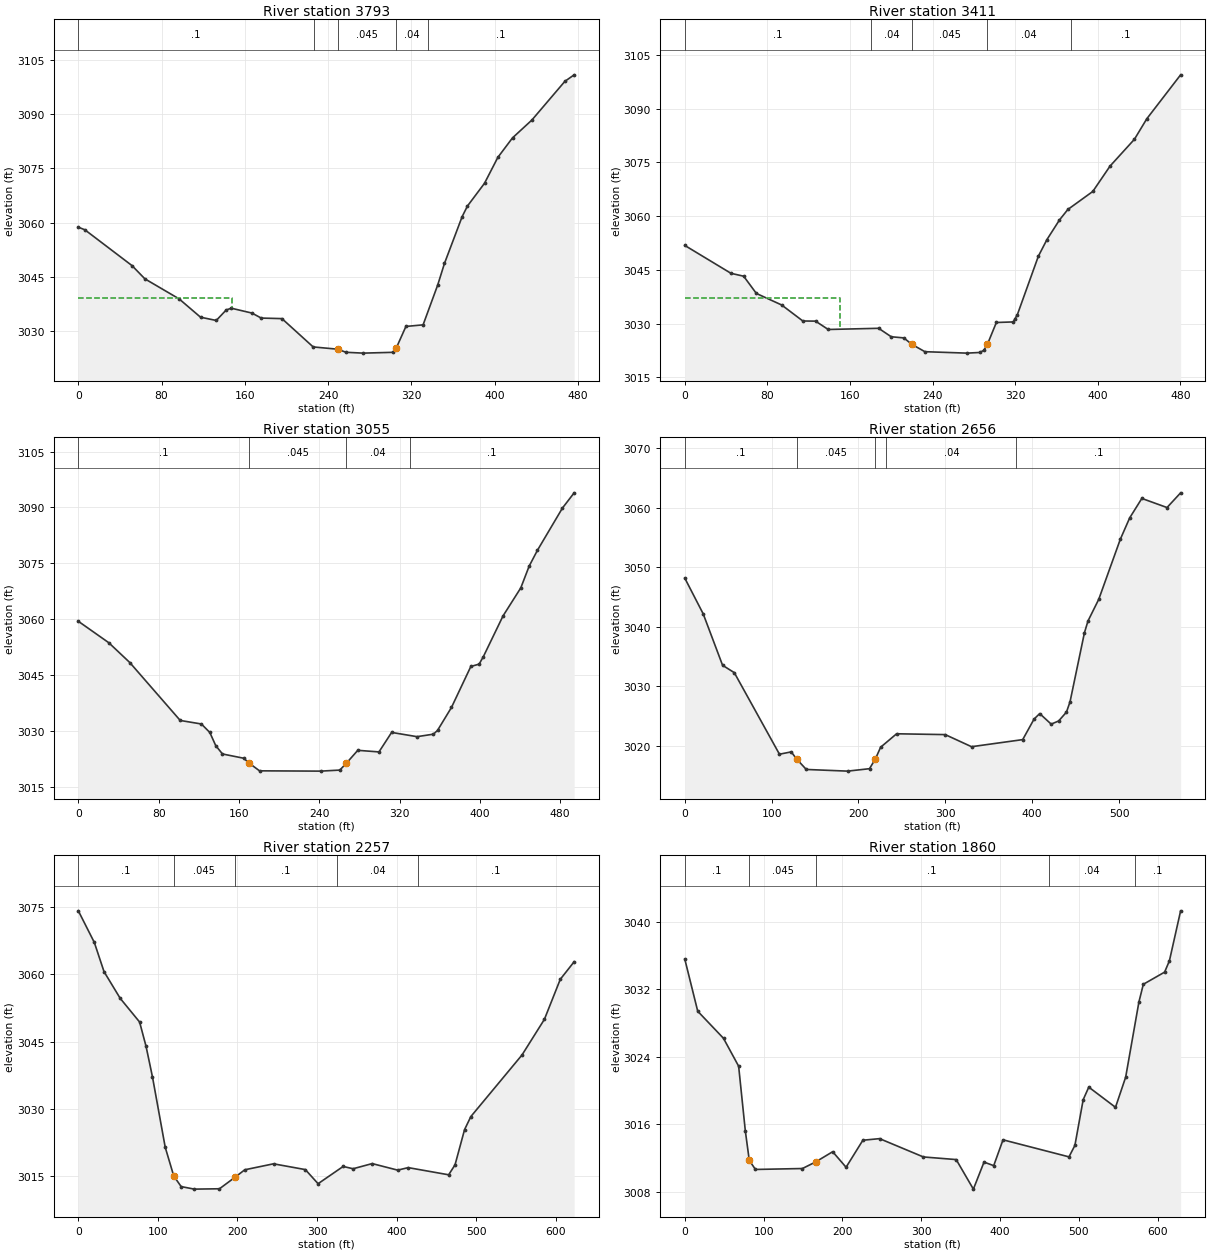
Type RM Length L Ch R = 1 ,3793    ,363.5,382.4,400.3
XS GIS Cut Line= 4
2154190.30878796461451.3755092272154048.18331208461485.760705005
 2153844.1644838461533.8999790942153731.83951092461577.454560412
#Sta/Elev= 30
       0 3058.75     6.3 3058.02    51.6 3048.13    63.9 3044.49    96.8 3038.95
   117.4 3033.89   132.5 3032.99   142.1  3035.9     147 3036.37   166.8 3035.03
   175.7 3033.65   195.6  3033.5   225.6 3025.68     249 3025.06   257.2  3024.2
   273.6 3023.97     302 3024.19   305.4 3025.36   314.7 3031.34   331.2 3031.78
   345.3 3042.83   351.7 3048.72   368.7 3061.65   373.8 3064.58   390.2 3070.87
     403 3078.02   417.1 3083.41   435.7 3088.33   467.4 3099.02476.3207 3100.82
#Mann= 5 ,-1,0
       0      .1       0  226.23     .04       0     249    .045       0
   305.4     .04       0  336.23      .1       0
#XS Ineff= 2 , 0
          147.96 3039.24
Permanent Ineff=
       F       F
Bank Sta=249,305.4
XS Rating Curve= 0 ,0
Exp/Cntr(USF)=0,0
Exp/Cntr=0.3,0.1

Type RM Length L Ch R = 1 ,3411    ,349.7,355.8,363.2
XS GIS Cut Line= 4
2154139.87716748461190.0480213172154002.33638437461160.247518309
2153773.10174586461116.6929369912153667.65381214461105.231205065
#Sta/Elev= 30
       0  3051.8    44.7 3044.02      57 3043.21    69.3  3038.4    93.8 3035.18
   114.3 3030.71   126.6 3030.67   138.9 3028.34   187.7 3028.67   199.9 3026.31
   212.1 3025.99  219.793024.202   232.5 3022.14   273.2 3021.74   285.5 3021.92
   289.5  3022.5  293.053024.203   301.7 3030.29     318 3030.45   319.7 3031.29
   322.1 3032.52   342.4 3048.81   350.7 3053.44   362.8  3058.9   370.9 3061.83
   395.1 3066.87   411.8 3073.95   435.4 3081.43   447.4 3087.16480.1368 3099.42
#Mann= 5 ,-1,0
       0      .1       0  180.73     .04       0  219.79    .045       0
  293.05     .04       0  374.07      .1       0
#XS Ineff= 2 , 0
          150.54 3037.06
Permanent Ineff=
       F       F
Bank Sta=219.79,293.05
XS Rating Curve= 0 ,0
Exp/Cntr(USF)=0,0
Exp/Cntr=0.3,0.1

Type RM Length L Ch R = 1 ,3055    ,394.3,398.6,402.5
XS GIS Cut Line= 4
2154181.13940242460859.9501418512154077.98381509460827.857292458
2153876.25733319460761.3792472882153708.91604707460715.532319585
#Sta/Elev= 30
       0 3059.47    30.3 3053.73    51.3  3048.4   101.5 3032.88   122.6 3031.93
     131 3029.65   136.9 3026.12   143.6 3023.89   164.7 3022.75  170.253021.419
   180.5 3019.37   241.5 3019.29   260.5 3019.57  267.053021.421   278.4 3024.87
   299.5 3024.44   312.1 3029.67   337.4 3028.53   353.7  3029.2   357.8  3030.2
   371.7 3036.36     391 3047.35   399.3 3047.99   403.5    3050   423.1 3060.92
   440.8 3068.44   449.1 3074.26   457.4 3078.53   482.3 3089.85493.9386 3093.92
#Mann= 4 ,-1,0
       0      .1       0  170.25    .045       0  267.05     .04       0
  330.43      .1       0
Bank Sta=170.25,267.05
XS Rating Curve= 0 ,0
Exp/Cntr(USF)=0,0
Exp/Cntr=0.3,0.1

Type RM Length L Ch R = 1 ,2656    ,416.5,399.2,379.9
XS GIS Cut Line= 4
2154275.12560421460495.4670666082154201.77051988460458.789524445
2153933.56599282460348.7568979562153741.00889646460298.325277482
#Sta/Elev= 30
       0 3048.17    21.2 3042.17    43.5 3033.54      57  3032.3     109 3018.61
   122.6    3019  128.733017.809   139.9 3016.05   187.5 3015.77   212.7 3016.18
  219.443017.807   225.5 3019.78   243.9 3022.04   299.9  3021.9   330.2 3019.87
   389.1 3021.06   402.2 3024.51   408.7 3025.43   421.9 3023.66   430.5 3024.19
   439.5 3025.68   443.6  3027.4   460.2    3039   464.3 3040.98   476.7 3044.62
   501.5 3054.69   512.3 3058.28   526.3 3061.55   555.3 3060.02570.9632 3062.49
#Mann= 5 ,-1,0
       0      .1       0  128.73    .045       0  219.44      .1       0
  232.01     .04       0  381.91      .1       0
Bank Sta=128.73,219.44
XS Rating Curve= 0 ,0
Exp/Cntr(USF)=0,0
Exp/Cntr=0.3,0.1

Type RM Length L Ch R = 1 ,2257    ,414.8,397.3,377.3
XS GIS Cut Line= 4
2154392.03526985460066.7982925792154298.04906806460050.751867883
2153977.12057414460043.8748287272153770.80939947460057.628907038
#Sta/Elev= 30
       0 3074.21    20.1 3067.15    32.3 3060.63    52.6 3054.68      77 3049.39
    85.1 3043.97    93.2 3037.11   109.2 3021.43  119.923015.022   129.2 3012.66
   145.7 3012.09   177.4 3012.17   196.6  3014.7   209.2 3016.41   245.3 3017.74
   285.3 3016.45   301.3  3013.3   332.8 3017.15   345.3 3016.64   369.3 3017.79
   401.3 3016.33   414.6 3016.89   465.4 3015.29   473.4 3017.51   485.4 3025.38
   493.3 3028.29   557.6 3042.04   585.7 3049.98   605.7 3058.93623.1175 3062.85
#Mann= 5 ,-1,0
       0      .1       0  119.92    .045       0   196.6      .1       0
  325.35     .04       0  426.35      .1       0
Bank Sta=119.92,196.6
XS Rating Curve= 0 ,0
Exp/Cntr(USF)=0,0
Exp/Cntr=0.3,0.1

Type RM Length L Ch R = 1 ,1860    ,414.9,402.3,379.4
XS GIS Cut Line= 4
2154291.17202891459617.4984010842154249.90979397459635.837172165
2154018.38280907459720.6539884172153718.08543261459874.241196224
#Sta/Elev= 30
       0 3035.58    16.4 3029.41    49.1  3026.2    68.3  3022.9    76.8 3015.22
    81.8 3011.75    89.6 3010.67   149.2 3010.78     166 3011.56   187.6 3012.77
   204.6 3010.93   225.9 3014.13   247.1 3014.32   302.7 3012.15   344.3 3011.84
   366.1 3008.34   379.6 3011.54   391.9 3011.12   403.7 3014.18   487.4 3012.16
   494.9 3013.52   505.4 3018.93   512.5 3020.42   546.4 3018.03   559.3  3021.6
   576.1  3030.5   581.7  3032.6   608.7 3034.04   614.8 3035.38629.0222  3041.3
#Mann= 5 ,-1,0
       0      .1       0    81.8    .045       0     166      .1       0
  461.73     .04       0  571.73      .1       0
Bank Sta=81.8,166
XS Rating Curve= 0 ,0
Exp/Cntr(USF)=0,0
Exp/Cntr=0.3,0.1