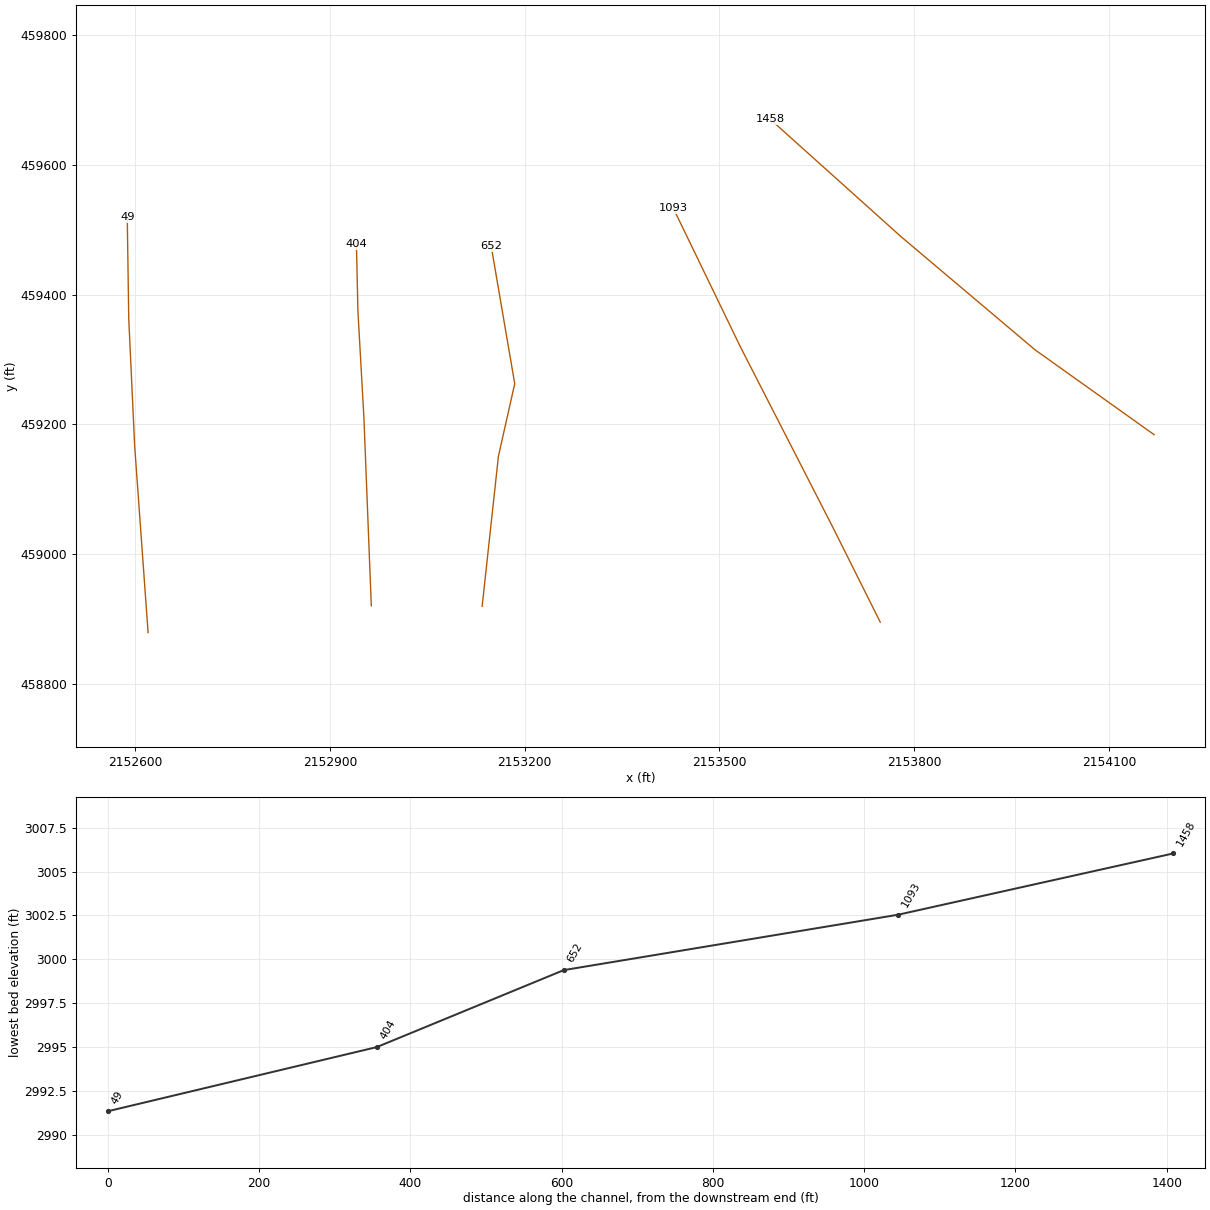
HEC-RAS study CRANBRYRV.prj: CRANBRYRV

--- CRANBRYRV.g01 (geometry) --- (continued)

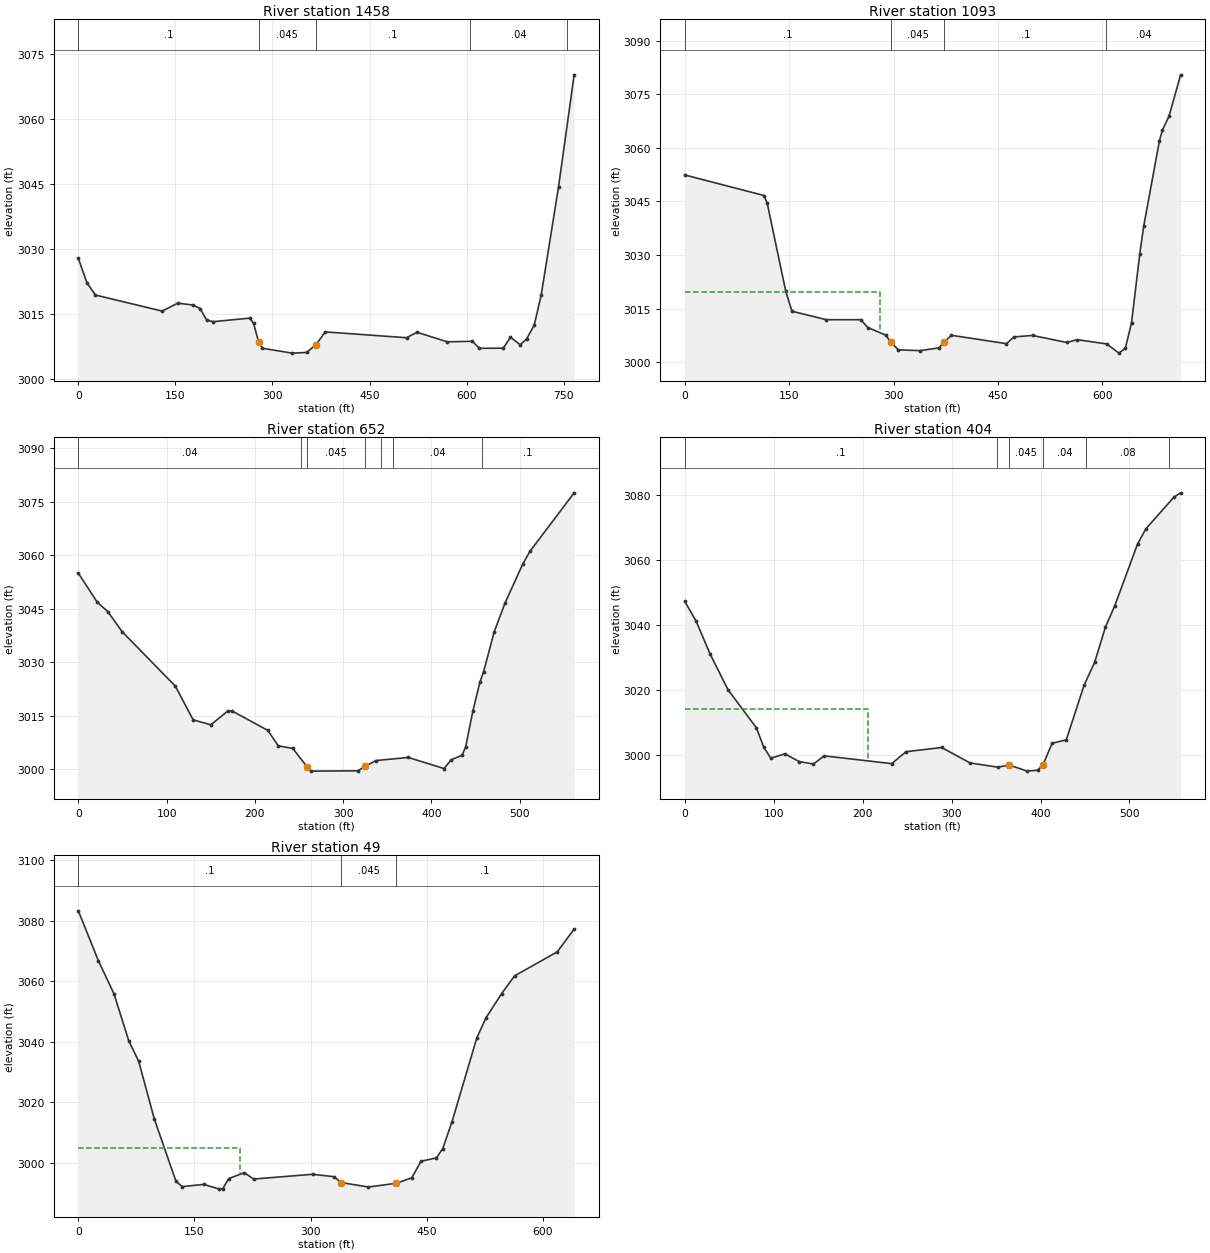
Type RM Length L Ch R = 1 ,1458    ,387.3,364.2,345.3
XS GIS Cut Line= 4
2154169.67767049459184.2449342852153986.28995968 459314.90867824
2153779.97878501459489.1270035142153578.25230312459670.222367943
#Sta/Elev= 30
       0 3027.87    13.2 3022.27    26.4 3019.42   129.5 3015.72   153.8 3017.55
   176.7 3017.13   188.2 3016.31   198.3 3013.66   208.2 3013.28   265.2  3014.1
   270.9 3012.86  278.853008.495   284.5 3007.15   330.5 3006.03   352.7 3006.18
   367.4 3007.99   381.6 3010.92   507.3 3009.58   523.4 3010.84   570.2 3008.63
   609.1 3008.76   619.7 3007.14   656.6 3007.17   667.9 3009.69   683.1 3007.95
   692.9 3009.33   704.6 3012.48   715.3 3019.37   742.2 3044.39766.2946 3070.17
#Mann= 5 ,-1,0
       0      .1       0  278.85    .045       0   367.4      .1       0
  605.21     .04       0  755.21      .1       0
Bank Sta=278.85,367.4
XS Rating Curve= 0 ,0
Exp/Cntr(USF)=0,0
Exp/Cntr=0.3,0.1

Type RM Length L Ch R = 1 ,1093    ,471.7,441.9,406.8
XS GIS Cut Line= 4
2153747.88593562458895.4092897532153674.53085129459042.119458404
2153532.40537541459319.4933710112153429.24978808459532.681584832
#Sta/Elev= 30
       0 3052.41   113.8 3046.66   118.3 3044.62   145.1 3019.84     154 3014.27
   203.4  3011.9   252.9  3011.9   263.1  3009.7   288.8 3007.58     2963005.638
   306.8 3003.45   338.3 3003.24   365.2 3004.01   373.1 3005.72   383.2 3007.53
   462.3 3005.19   473.1 3007.08   499.8 3007.49   548.7 3005.53     564  3006.3
   606.4 3005.11   623.9 3002.54   633.1 3003.92     642 3011.07   653.8 3030.29
   659.6 3038.22     682 3061.91   686.4 3065.02   695.7 3068.78712.5272 3080.44
#Mann= 4 ,-1,0
       0      .1       0     296    .045       0   373.1      .1       0
  605.69     .04       0
#XS Ineff= 2 , 0
          280.18 3019.52
Permanent Ineff=
       F       F
Bank Sta=296,373.1
XS Rating Curve= 0 ,0
Exp/Cntr(USF)=0,0
Exp/Cntr=0.3,0.1

Type RM Length L Ch R = 1 ,652     ,244.2,247.2,253.2
XS GIS Cut Line= 4
2153134.65345365458919.8604617492153159.73708575459151.187291043
2153184.82071784459262.6701003422153148.58880482459474.487438008
#Sta/Elev= 30
       0 3054.94    21.4 3046.81    33.5 3044.12    49.6 3038.53     110 3023.22
   130.1 3013.77   150.2  3012.4   169.6 3016.32   174.3 3016.25   214.6 3010.84
   226.6 3006.48   242.9 3005.78   259.3 3000.57   263.4 2999.39   316.7 2999.48
   325.1 3000.74   337.2 3002.36   373.9 3003.22   414.4 3000.11   422.5 3002.59
   434.7 3003.82   438.8 3006.13   447.1 3016.33     455 3024.37   459.1 3027.22
   471.2 3038.47   483.4 3046.52   503.7 3057.59   511.8 3061.11   561.8 3077.49
#Mann= 7 ,-1,0
       0     .04       0  252.68      .1       0   259.3    .045       0
   325.1      .1       0  342.68     .06       0  356.95     .04       0
  456.95      .1       0
Bank Sta=259.3,325.1
XS Rating Curve= 0 ,0
Exp/Cntr(USF)=0,0
Exp/Cntr=0.3,0.1

Type RM Length L Ch R = 1 ,404     ,358.9,355.6,354.5
XS GIS Cut Line= 4
2152963.90347189 458920.625099992152952.44173996459211.753090907
2152943.27235442459374.5096842552152940.98000804459477.665271588
#Sta/Elev= 30
       0 3047.28    12.6  3041.3    28.6 3031.01    48.6 3020.08    80.6 3008.33
    88.6 3002.52    96.6    2999   112.6 3000.32   128.7 2997.94   144.7  2997.2
   156.7 2999.71   232.7 2997.32   248.7 3000.99   288.8 3002.29   320.8 2997.53
     352 2996.23   364.8  2996.9   384.9 2995.01   396.9  2995.3   402.9 2997.05
     413 3003.57     429 3004.67     449 3021.48     461 3028.64     473 3039.38
   483.5 3045.96   509.1 3064.97   518.7 3069.75     550  3079.4557.5493 3080.75
#Mann= 6 ,-1,0
       0      .1       0  351.35     .04       0   364.8    .045       0
   402.9     .04       0  451.35     .08       0  544.37      .1       0
#XS Ineff= 2 , 0
          206.45 3014.19
Permanent Ineff=
       F       F
Bank Sta=364.8,402.9
XS Rating Curve= 0 ,0
Exp/Cntr(USF)=0,0
Exp/Cntr=0.3,0.1

Type RM Length L Ch R = 1 ,49      ,,,
XS GIS Cut Line= 4
2152620.05151411458879.3628650562152599.42039664459165.906163204
 2152590.2510111459363.0479523292152587.95866472459518.927506521
#Sta/Elev= 30
       0  3083.3    25.9 3066.82    45.9 3055.98    65.2 3040.35      78 3033.56
    98.1 3014.59   126.1 2993.97   134.2  2992.2   162.2 2992.92   182.3 2991.36
   186.3 2991.42   194.3 2994.86   214.4 2996.79   226.4 2994.69   302.6 2996.26
   330.6 2995.46   339.4 2993.54   374.7 2992.06   410.7 2993.29   430.7 2995.08
   442.7 3000.57   462.7 3001.69   470.8 3004.77   482.8 3013.67   514.8 3041.34
   526.8 3048.03   546.8 3055.95   563.7 3061.84   618.7 3069.75640.5364 3077.28
#Mann= 3 ,-1,0
       0      .1       0   339.4    .045       0   410.7      .1       0
#XS Ineff= 2 , 0
          209.46 3004.91
Permanent Ineff=
       F       F
Bank Sta=339.4,410.7
XS Rating Curve= 0 ,0
Exp/Cntr(USF)=0,0
Exp/Cntr=0.3,0.1
LCMann Table=0

Chan Stop Cuts=-1
Use User Specified Reach Order=0
Composite Channel Slope=5